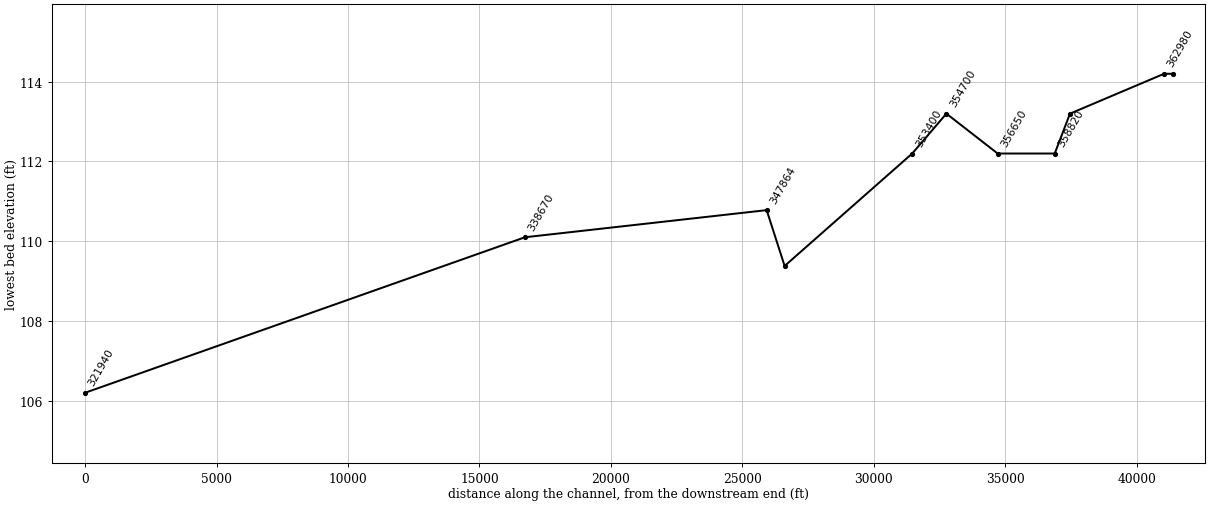
--- Wateree_River.prj (project) ---

Proj Title=Wateree_River
Current Plan=p04
Default Exp/Contr=0.3,0.1
English Units
Geom File=g12
Geom File=g13
Geom File=g14
Geom File=g15
Flow File=f01
Plan File=p02
Plan File=p03
Plan File=p01
Plan File=p04
Y Axis Title=Elevation
X Axis Title(PF)=Main Channel Distance
X Axis Title(XS)=Station
BEGIN DESCRIPTION:
END DESCRIPTION:
DSS File=dss
DSS Export Rating Curves= 0
DSS Export Rating Curve Sorted= 0
DSS Export Volume Flow Curves= 0
DXF OffsetX= 0
DXF OffsetY= 0
DXF ScaleX= 1
DXF ScaleY= 10

--- Wateree_River.p04 (plan) ---

Plan Title=Revised Conditions
Program Version=5.07
Short Identifier=Revised
Geom File=g15
Flow File=f01
Subcritical Flow
K Sum by GR= 0
Std Step Tol= 0.01
Critical Tol= 0.01
Num of Std Step Trials= 20
Max Error Tol= 0.3
Flow Tol Ratio= 0.001
Split Flow NTrial= 30
Split Flow Tol= 0.02
Split Flow Ratio= 0.02
Log Output Level= 0
Friction Slope Method= 1
Unsteady Friction Slope Method= 2
Unsteady Bridges Friction Slope Method= 1
Parabolic Critical Depth
Global Vel Dist= 0 , 0 , 0
Global Log Level= 0
CheckData=True
Encroach Param=-1 ,0,0, 2
Encroach River=River 1
Encroach Reach=Reach 1
Encroach Node=363310
       116332.6118296.34
Encroach Node=362980
       116167.9217954.89
Encroach Node=359400
       116079.59   17866
Encroach Node=358820
       116128.46   17935
Encroach Node=356650
       116674.6419530.46
Encroach Node=354700
       1   1725919822.43
Encroach Node=353400
       114800.07 19791.8
Encroach Node=348547
       1    7550   19640
Encroach Node=347864
       1    7030   19640
Encroach Node=338670
       1   1575024855.88
Encroach Node=321940
       1    4286   25736
Computation Interval=1MIN
Output Interval=1HOUR
Instantaneous Interval=1HOUR
Mapping Interval=1HOUR
Computation Time Step Use Courant=        0
Computation Time Step Use Time Series=    0
Computation Time Step Count To Double=0
Computation Time Step Max Doubling=0
Computation Time Step Max Halving=0
Computation Time Step Residence Courant=0
Run HTab= 0
Run UNet= 0
Run Sediment= 0
Run PostProcess= 0
Run WQNet= 0
Run RASMapper= 0
UNET Theta= 1
UNET Theta Warmup= 1
UNET ZTol= 0.02
UNET ZSATol= 0.02
UNET MxIter= 20
UNET Max Iter WO Improvement= 0
UNET MaxInSteps= 0
UNET DtIC= 0
UNET DtMin= 0
UNET MaxCRTS= 20
UNET WFStab= 2
UNET SFStab= 1
UNET WFX= 1
UNET SFX= 1
UNET 1D Methodology=Finite Difference
UNET DSS MLevel= 4
UNET Pardiso=0
UNET DZMax Abort= 100
UNET Use Existing IB Tables=-1
UNET Froude Reduction=False
UNET Froude Limit= 0.8
UNET Froude Power= 4
UNET D1 Cores= 0
UNET D2 Coriolis=0
UNET D2 Cores= 0
UNET D2 Theta= 1
UNET D2 Theta Warmup= 1
UNET D2 Z Tol= 0.01
UNET D2 Volume Tol= 0.01
UNET D2 Max Iterations= 20
UNET D2 Equation= 0
UNET D2 RampUpFraction=0.1
UNET D2 TimeSlices= 1
UNET D2 BCVolumeCheck=0
UNET D1D2 MaxIter= 0
UNET D1D2 ZTol=0.01
UNET D1D2 QTol=0.1
UNET D1D2 MinQTol=1
Write IC File= 0
Write IC File at Fixed DateTime=0
Write IC File at Sim End=0
Echo Input=False
Echo Parameters=False
Echo Output=False
Write Detailed= 0
HDF Write Warmup=0
HDF Write Time Slices=0
HDF Flush=0
HDF Face Node Velocities=0
HDF Compression= 1
HDF Chunk Size= 1
HDF Spatial Parts= 1
HDF Use Max Rows=0
HDF Fixed Rows= 1
Calibration Method= 0
Calibration Iterations= 20
Calibration Max Change=0.05
Calibration Tolerance=0.2
Calibration Maximum=1.5
Calibration Minimum=0.5
Calibration Optimization Method= 1
WQ AD Non Conservative
WQ ULTIMATE=-1
WQ Max Comp Step=1HOUR
WQ Output Interval=15MIN
WQ Output Selected Increments= 0
WQ Output face flow=0
WQ Output face velocity=0
WQ Output face area=0
WQ Output face dispersion=0
WQ Output cell volume=0
WQ Output cell surface area=0
WQ Output cell continuity=0
WQ Output cumulative cell continuity=0
WQ Output face conc=0
WQ Output face dconc_dx=0
WQ Output face courant=0
WQ Output face peclet=0
WQ Output face adv mass=0
WQ Output face disp mass=0
WQ Output cell mass=0
WQ Output cell source sink temp=0
WQ Output nsm pathways=0
WQ Output nsm derived pathways=0
WQ Output MaxMinRange=-1
WQ Daily Max Min Mean=-1
WQ Daily Range=0
WQ Daily Time=0
WQ Create Restart=0
WQ Fixed Restart=0
WQ System Summary=0
WQ Write To DSS=0
WQ Use Fixed Temperature=0
Sorting and Armoring Iterations= 10
XS Update Threshold= 0.02
Bed Roughness Predictor= 0
Hydraulics Update Threshold= 0.02
Energy Slope Method= 1
Volume Change Method= 1
Sediment Retention Method= 0
XS Weighting Method= 0
Number of US Weighted Cross Sections= 1
Number of DS Weighted Cross Sections= 1
Upstream XS Weight=0
Main XS Weight=1
Downstream XS Weight=0
Number of DS XS's Weighted with US Boundary= 1
Upstream Boundary Weight= 1
Weight of XSs Associated with US Boundary= 0
Number of US XS's Weighted with DS Boundary= 1
Downstream Boundary Weight= 0.5
Weight of XSs Associated with DS Boundary= 0.5
Percentile Method= 0
Sediment Output Level= 3
Mass or Volume Output= 0
Output Increment Type= 1
Profile and TS Output Increment= 1
XS Output Flag= 0
XS Output Increment= 10
Write Gradation File= 0
Read Gradation Hotstart= 0
Write HDF5 File= 1
Write Binary Output= 1
Write DSS Sediment File= 0
SV Curve= 0
Specific Gage Flag= 0

--- Wateree_River.p01 (plan) ---

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Plan Title=Existing Conditions
Short Identifier=EX
Geom File=g14
Flow File=f01

--- Wateree_River.p02 (plan) ---

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Plan Title=Duplicate Effective
Short Identifier=DE
Geom File=g12
Flow File=f01
K Sum by GR=-1
Encroach Param=-1 ,0,0, 0

--- Wateree_River.p03 (plan) ---

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Plan Title=Corrected Effective
Short Identifier=CE
Geom File=g13
Flow File=f01
Encroach Node=349270
       1 8256.97 17219.1
Encroach Node=345630
       1    800019371.07

--- Wateree_River.f01 (steady flow) ---

Flow Title=Duplicate Effective
Program Version=5.07
BEGIN FILE DESCRIPTION:
FEMA FIS for Kershaw County (10/28/2108)
END FILE DESCRIPTION:
Number of Profiles= 5
Profile Names=100-YR,FW,10-YR,50-YR,500-YR
River Rch & RM=River 1,Reach 1         ,363310
  224500  224500   89400  178500  421300
Boundary for River Rch & Prof#=River 1,Reach 1         , 1
Up Type= 0
Dn Type= 1
Dn Known WS=143.2
Boundary for River Rch & Prof#=River 1,Reach 1         , 2
Up Type= 0
Dn Type= 1
Dn Known WS=144.2
Boundary for River Rch & Prof#=River 1,Reach 1         , 3
Up Type= 0
Dn Type= 1
Dn Known WS=137.8
Boundary for River Rch & Prof#=River 1,Reach 1         , 4
Up Type= 0
Dn Type= 1
Dn Known WS=141.5
Boundary for River Rch & Prof#=River 1,Reach 1         , 5
Up Type= 0
Dn Type= 1
Dn Known WS=148
DSS Import GetInterval= 0
DSS Import GetPeak= 0
DSS Import FillOption= 0

--- Wateree_River.g15 (geometry) ---

Geom Title=Revised Conditions
Program Version=5.07

River Reach=River 1         ,Reach 1
Reach XY= 2
  2099039.164679  883566.6851846  2113070.050707  849841.0727428

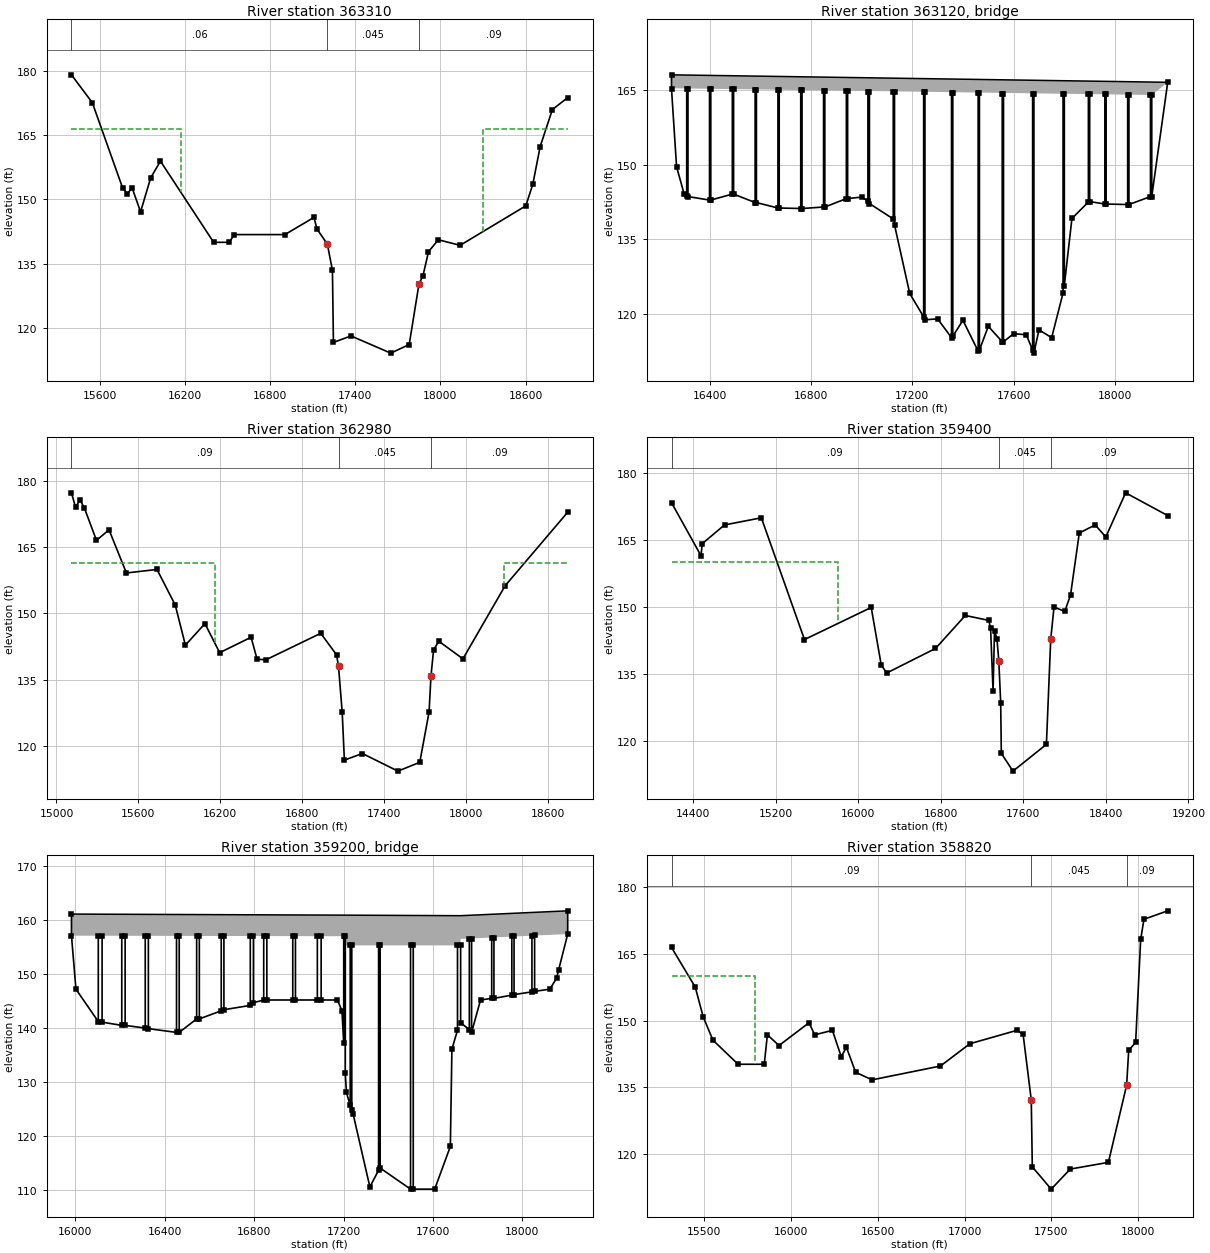
Type RM Length L Ch R = 1 ,363310  ,330,330,330
BEGIN DESCRIPTION:
LETTERED G
END DESCRIPTION:
#Sta/Elev= 30
   15400     179   15547   172.5   15760   152.7   15794   151.3   15827   152.7
   15887   147.1   15958     155   16027   158.9   16402     140   16513     140
   16546   141.8   16904   141.8   17109   145.8   17130   143.1   17203   139.6
   17239   133.5   17246   116.7   17370   118.2   17650   114.2   17780   116.2
   17849   130.3   17877   132.2   17916   137.8   17985   140.6   18139   139.3
   18602   148.5   18651   153.5   18703   162.3   18789   170.9   18897   173.7
#Mann= 3 , 0 , 0
   15400     .06       0   17203    .045       0   17849     .09       0
#XS Ineff= 2 , 0
       0   16170   166.5   18300       0   166.5
Permanent Ineff=
       F       F
Bank Sta=17203,17849
XS Rating Curve= 0 ,0
Exp/Cntr=0.5,0.3

Type RM Length L Ch R = 3 ,363120  ,,,
Bridge Culvert--1,0,-1,-1, 0
Deck Dist Width WeirC Skew NumUp NumDn MinLoCord MaxHiCord MaxSubmerge Is_Ogee
80,110,2.6,0, 2, 2, , , 0.98, 0, 0,0,,
   16250   18208
   168.1   166.6
   165.4     164
   16250   18208
   168.1   166.6
   165.4     164
BR Coef=-1 , 0 , 0 ,, 0 ,,,0.8,-1,,0,
WSPro=,,,, 1 ,,,, 0 ,,,, 0 ,,,,-1 ,-1 ,-1 , 0 , 0 , 0 , 0 , 0
BR U #Sta/Elev= 95
   16250     168   16250   165.3   16270   149.6   16300   144.1   16310   143.7
   16310   165.3   16315   165.3   16315   143.6   16400   142.9   16400   165.2
   16405   165.2   16405   142.9   16490   144.1   16490   165.2   16495   165.2
   16495   144.1   16580   142.4   16580   165.1   16585   165.1   16585   142.4
   16670   141.3   16670     165   16675     165   16675   141.3   16760   141.2
   16760     165   16765     165   16765   141.2   16850   141.5   16850   164.9
   16855   164.9   16855   141.5   16940   143.2   16940   164.8   16945   164.8
   16945   143.2   17000   143.5   17025   142.7   17025   164.7   17031   164.7
   17031   142.2   17125   139.1   17125   164.7   17130   164.7   17130   137.9
   17190   124.1   17245   119.4   17245   164.6   17250   164.6   17250   118.8
   17300     119   17355   115.2   17355   164.5   17360   164.5   17360   115.5
   17400   118.7   17460   112.5   17460   164.4   17465   164.4   17465   112.7
   17500   117.5   17555   114.4   17555   164.3   17560   164.3   17560   114.4
   17600     116   17650   115.8   17675   112.7   17675   164.2   17680   164.2
   17680   112.1   17700   116.8   17750   115.2   17795   124.2   17795   164.2
   17800   164.2   17800   125.7   17830   139.2   17895   142.5   17895   164.2
   17900   164.2   17900   142.6   17960   142.1   17960   164.2   17965   164.2
   17965   142.1   18050     142   18050   164.1   18055   164.1   18055     142
   18140   143.6   18140     164   18145     164   18145   143.6   18208   166.6
BR U #Mann= 3
   16250     .06   17025     .05   17900     .06
BR U Banks=17025,17900
BR D #Sta/Elev= 95
   16250     168   16250   165.3   16270   149.6   16300   144.1   16310   143.7
   16310   165.3   16315   165.3   16315   143.6   16400   142.9   16400   165.2
   16405   165.2   16405   142.9   16490   144.1   16490   165.2   16495   165.2
   16495   144.1   16580   142.4   16580   165.1   16585   165.1   16585   142.4
   16670   141.3   16670     165   16675     165   16675   141.3   16760   141.2
   16760     165   16765     165   16765   141.2   16850   141.5   16850   164.9
   16855   164.9   16855   141.5   16940   143.2   16940   164.8   16945   164.8
   16945   143.2   17000   143.5   17025   142.7   17025   164.7   17031   164.7
   17031   142.2   17125   139.1   17125   164.7   17130   164.7   17130   137.9
   17190   124.1   17245   119.4   17245   164.6   17250   164.6   17250   118.8
   17300     119   17355   115.2   17355   164.5   17360   164.5   17360   115.5
   17400   118.7   17460   112.5   17460   164.4   17465   164.4   17465   112.7
   17500   117.5   17555   114.4   17555   164.3   17560   164.3   17560   114.4
   17600     116   17650   115.8   17675   112.7   17675   164.2   17680   164.2
   17680   112.1   17700   116.8   17750   115.2   17795   124.2   17795   164.2
   17800   164.2   17800   125.7   17830   139.2   17895   142.5   17895   164.2
   17900   164.2   17900   142.6   17960   142.1   17960   164.2   17965   164.2
   17965   142.1   18050     142   18050   164.1   18055   164.1   18055     142
   18140   143.6   18140     164   18145     164   18145   143.6   18208   166.6
BR D #Mann= 3
   16250     .06   17025     .05   17900     .06
BR D Banks=17025,17900
BC Design=,, 0 ,, 0 ,,,,,,
BC Use User HTab Curves=0
BC User HTab FreeFlow(D)= 0

Type RM Length L Ch R = 1 ,362980  ,3500,3580,3530
#Sta/Elev= 30
   15110   177.4   15140   174.1   15172   175.8   15204     174   15293   166.6
   15385     169   15512   159.2   15736     160   15870   151.9   15944   142.8
   16087   147.7   16195   141.1   16425   144.6   16469   139.6   16535   139.5
   16935   145.5   17051   140.6   17065     138   17092   127.6   17108   116.7
   17240   118.2   17500   114.2   17660   116.2   17728   127.6   17742   135.8
   17761   141.7   17799   143.7   17976   139.7   18285   156.3   18743     173
#Mann= 3 , 0 , 0
   15110     .09       0   17065    .045       0   17742     .09       0
#XS Ineff= 2 , 0
       0   16160   161.5   18278       0   161.5
Permanent Ineff=
       F       F
Bank Sta=17065,17742
XS Rating Curve= 0 ,0
Exp/Cntr=0.5,0.3

Type RM Length L Ch R = 1 ,359400  ,520,580,570
#Sta/Elev= 30
   14190   173.4   14476   161.5   14488   164.2   14704   168.4   15061     170
   15479   142.7   16126   149.9   16223     137   16276   135.2   16749   140.7
   17038   148.1   17265     147   17283   145.3   17307   131.1   17321   144.7
   17345   142.8   17363   137.8   17381   128.5   17387   117.2   17500   113.2
   17824   119.2   17866   142.8   17898     150   18002     149   18058   152.7
   18143   166.6   18297   168.4   18400   165.7   18592   175.6   19000   170.5
#Mann= 3 , 0 , 0
   14190     .09       0   17363    .045       0   17866     .09       0
#XS Ineff= 2 , 0
       0   15803     160   18383       0     160
Permanent Ineff=
       F       F
Bank Sta=17363,17866
XS Rating Curve= 0 ,0
Exp/Cntr=0.5,0.3

Type RM Length L Ch R = 3 ,359200  ,,,
Bridge Culvert--1,0,-1,-1, 0
Deck Dist Width WeirC Skew NumUp NumDn MinLoCord MaxHiCord MaxSubmerge Is_Ogee
180,20,2.6,0, 6, 6, , , 0.98, 0, 0,0,,
   15983   17208   17208   17724   17724   18203
   161.1   160.9   160.9   160.8   160.8   161.7
   157.1     157   155.3   155.3   156.5   157.4
   15983   17208   17208   17724   17724   18203
   161.1   160.9   160.9   160.8   160.8   161.7
   157.1     157   155.3   155.3   156.5   157.4
BR Coef=-1 , 0 , 0 ,, 0 ,,,0.8,-1,,0,
WSPro=,,,, 1 ,,,, 0 ,,,, 0 ,,,,-1 ,-1 ,-1 , 0 , 0 , 0 , 0 , 0
BR U #Sta/Elev= 93
   15983   161.1   15983   157.1   16003   147.2   16103   141.2   16103   157.1
   16120   157.1   16120   141.1   16208   140.5   16208   157.1   16223   157.1
   16223   140.5   16313     140   16313   157.1   16327   157.1   16327   139.9
   16453   139.2   16453     157   16465     157   16465   139.2   16543   141.7
   16543     157   16555     157   16555   141.7   16653   143.2   16653     157
   16665     157   16665   143.4   16783   144.2   16783     157   16797     157
   16797   144.7   16843   145.2   16843     157   16857     157   16857   145.2
   16973   145.2   16973     157   16985     157   16985   145.2   17083   145.2
   17083     157   17100     157   17100   145.2   17173   145.2   17193   143.2
   17201   137.2   17201     157   17208     157   17208   131.6   17213   128.1
   17230   125.7   17230   155.3   17237   155.3   17237   124.9   17243   124.1
   17318   110.6   17357   113.7   17357   155.3   17364   155.3   17364   114.1
   17500   110.2   17500   155.3   17512   155.3   17512   110.2   17608   110.2
   17678   118.1   17685   136.1   17710   139.6   17710   155.3   17724   155.3
   17724     141   17763   139.7   17763   156.5   17773   156.5   17773   139.2
   17813   145.2   17863   145.5   17863   156.7   17873   156.7   17873   145.5
   17953   146.1   17953     157   17963     157   17963   146.2   18043   146.7
   18043   157.1   18055   157.2   18055   146.8   18123   147.2   18153   149.2
   18162   150.7   18203   157.4   18203   161.7
BR U #Mann= 3
   15983     .06   17193    .045   17724     .06
BR U Banks=17193,17724
BR D #Sta/Elev= 93
   15983   161.1   15983   157.1   16003   147.2   16103   141.2   16103   157.1
   16120   157.1   16120   141.1   16208   140.5   16208   157.1   16223   157.1
   16223   140.5   16313     140   16313   157.1   16327   157.1   16327   139.9
   16453   139.2   16453     157   16465     157   16465   139.2   16543   141.7
   16543     157   16555     157   16555   141.7   16653   143.2   16653     157
   16665     157   16665   143.4   16783   144.2   16783     157   16797     157
   16797   144.7   16843   145.2   16843     157   16857     157   16857   145.2
   16973   145.2   16973     157   16985     157   16985   145.2   17083   145.2
   17083     157   17100     157   17100   145.2   17173   145.2   17193   143.2
   17201   137.2   17201     157   17208     157   17208   131.6   17213   128.1
   17230   125.7   17230   155.3   17237   155.3   17237   124.9   17243   124.1
   17318   110.6   17357   113.7   17357   155.3   17364   155.3   17364   114.1
   17500   110.2   17500   155.3   17512   155.3   17512   110.2   17608   110.2
   17678   118.1   17685   136.1   17710   139.6   17710   155.3   17724   155.3
   17724     141   17763   139.7   17763   156.5   17773   156.5   17773   139.2
   17813   145.2   17863   145.5   17863   156.7   17873   156.7   17873   145.5
   17953   146.1   17953     157   17963     157   17963   146.2   18043   146.7
   18043   157.1   18055   157.2   18055   146.8   18123   147.2   18153   149.2
   18162   150.7   18203   157.4   18203   161.7
BR D #Mann= 3
   15983     .06   17193    .045   17724     .06
BR D Banks=17193,17724
BC Design=,, 0 ,, 0 ,,,,,,
BC Use User HTab Curves=0
BC User HTab FreeFlow(D)= 0

Type RM Length L Ch R = 1 ,358820  ,1800,2170,2200
BEGIN DESCRIPTION:
LETTERED F
END DESCRIPTION:
#Sta/Elev= 30
   15310   166.4   15447   157.5   15493   150.8   15549   145.6   15694   140.2
   15845   140.2   15863   146.8   15930   144.4   16103   149.5   16136   146.8
   16238   147.8   16289   141.9   16319     144   16372   138.4   16467   136.7
   16861   139.8   17031   144.8   17302   147.8   17338   146.9   17385   132.2
   17391   117.2   17500   112.2   17610   116.7   17830   118.2   17935   135.5
   17947   143.3   17987   145.1   18016   168.2   18035   172.7   18172   174.6
#Mann= 3 , 0 , 0
   15310     .09       0   17385    .045       0   17935     .09       0
#XS Ineff= 2 , 0
       0   15793     160   18393       0     160
Permanent Ineff=
       F       F
Bank Sta=17385,17935
XS Rating Curve= 0 ,0
Exp/Cntr=0.5,0.3

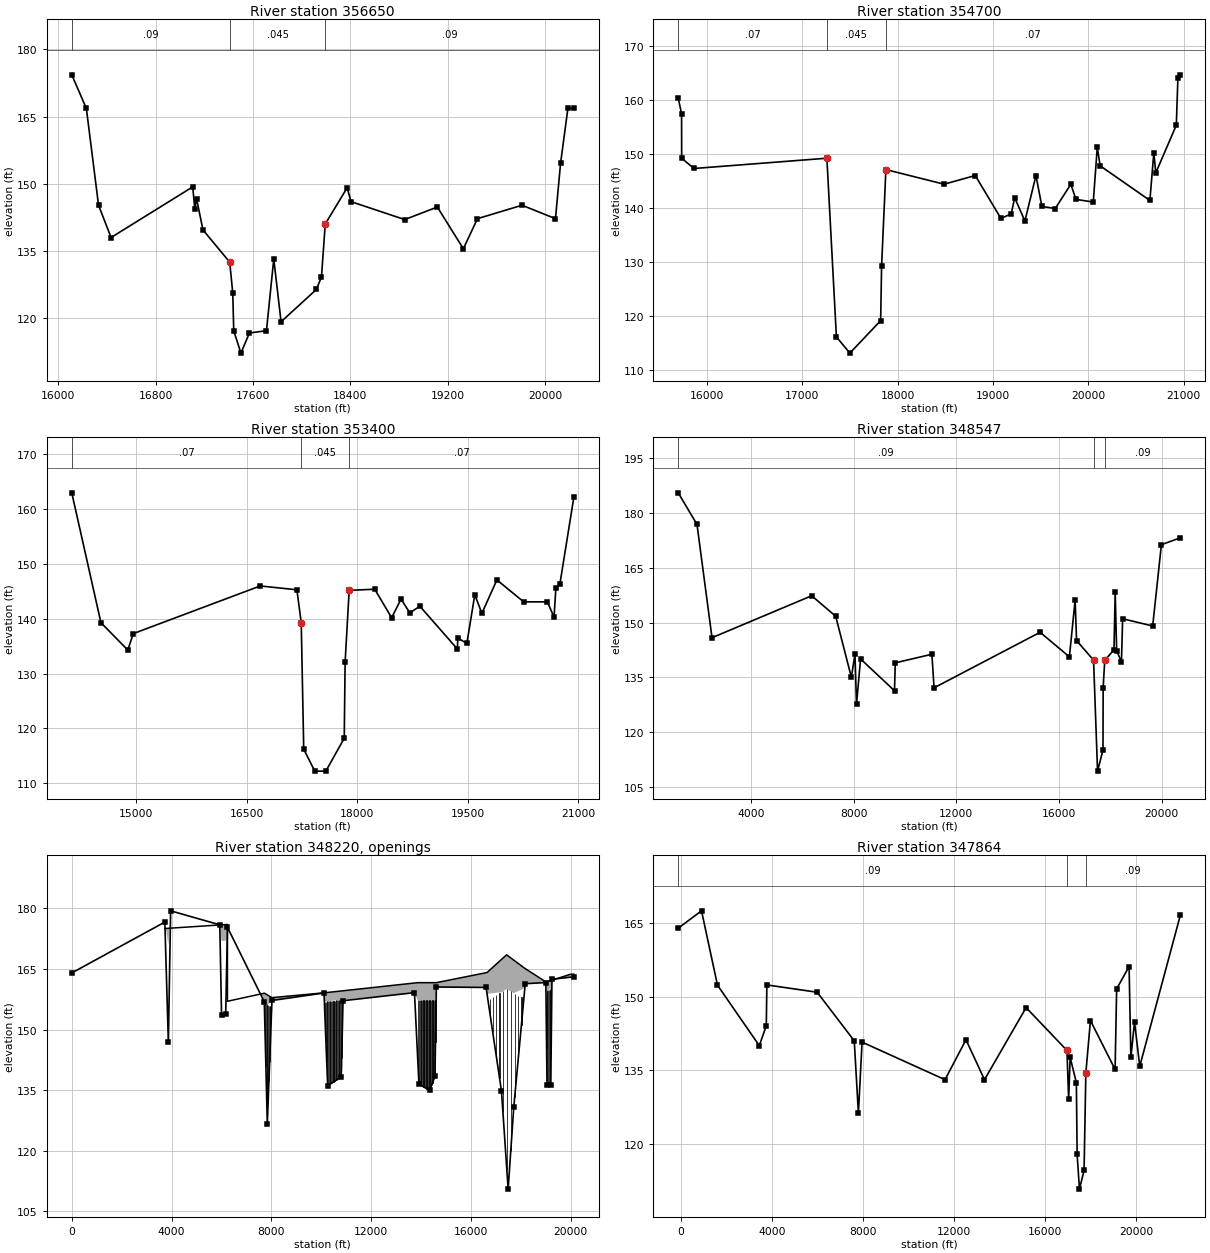
Type RM Length L Ch R = 1 ,356650  ,2400,1950,1200
#Sta/Elev= 30
   16110   174.3   16230   166.8   16330   145.2   16433     138   17104   149.3
   17121   144.4   17136   146.6   17188   139.7   17408   132.5   17433   125.6
   17441   117.2   17500   112.2   17570   116.7   17710   117.2   17770   133.2
   17830   119.2   18120   126.4   18162   129.2   18193     141   18373   149.1
   18405     146   18846     142   19114   144.8   19328   135.5   19444   142.2
   19810   145.2   20085   142.2   20127   154.6   20187   166.8   20236   166.8
#Mann= 3 , 0 , 0
   16110     .09       0   17408    .045       0   18193     .09       0
Bank Sta=17408,18193
XS Rating Curve= 0 ,0
Exp/Cntr=0.3,0.1

Type RM Length L Ch R = 1 ,354700  ,1500,1300,1000
#Sta/Elev= 30
   15700   160.3   15735   157.4   15736   149.2   15865   147.3   17259   149.2
   17359   116.2   17500   113.2   17823   119.2   17833   129.3   17878   147.1
   18488   144.4   18815     146   19084   138.1   19192   138.9   19229   141.9
   19336   137.6   19452     146   19514   140.3   19654   139.9   19818   144.4
   19871   141.6   20053   141.1   20095   151.2   20125   147.8   20647   141.4
   20688   150.2   20709   146.5   20924   155.3   20941   164.1   20966   164.6
#Mann= 3 , 0 , 0
   15700     .07       0   17259    .045       0   17878     .07       0
Bank Sta=17259,17878
XS Rating Curve= 0 ,0
Exp/Cntr=0.3,0.1

Type RM Length L Ch R = 1 ,353400  ,5123,4853,3823
BEGIN DESCRIPTION:
LETTERED E
END DESCRIPTION:
#Sta/Elev= 30
   14125     163   14521   139.3   14886   134.3   14960   137.3   16684     146
   17182   145.3   17241   139.3   17275   116.2   17425   112.2   17575   112.2
   17825   118.2   17837   132.1   17892   145.2   18239   145.4   18469   140.2
   18596   143.6   18716   141.1   18852   142.3   19361   134.5   19368   136.5
   19490   135.5   19598   144.4   19694     141   19898   147.1   20262   143.1
   20584   143.1   20674   140.3   20699   145.6   20754   146.4   20943   162.2
#Mann= 3 , 0 , 0
   14125     .07       0   17241    .045       0   17892     .07       0
Bank Sta=17241,17892
XS Rating Curve= 0 ,0
Exp/Cntr=0.3,0.1

Type RM Length L Ch R = 1 ,348547  ,500,683,200
#Sta/Elev= 30
  1171.4  185.47  1902.3  176.82  2486.1  145.86    6368  157.33  7303.1  151.72
  7913.2  135.03  8053.2  141.36  8113.2   127.6  8271.4  140.06  9593.4  131.35
  9622.1  138.98 11048.6  141.34 11133.7  132.16   15263  147.34 16402.7  140.63
 16626.6  156.09 16683.3  145.07 17344.2  139.73   17500  109.38 17711.5  115.18
 17717.4  132.09 17779.6  139.65   18140  142.58 18186.6  158.32 18243.6  142.34
 18430.2  139.24 18476.9  151.04 19646.8  149.06 19985.3  171.2820722.61  173.18
#Mann= 3 , 0 , 0
  1171.4     .09       0 17344.2    .045       0 17779.6     .09       0
Bank Sta=17344.2,17779.6
XS Rating Curve= 0 ,0
Exp/Cntr(USF)=0,0
Exp/Cntr=0.5,0.3

Type RM Length L Ch R = 4 ,348220  ,,,
Bridge Culvert--1,0,-1,-1, 0
Deck Dist Width WeirC Skew NumUp NumDn MinLoCord MaxHiCord MaxSubmerge Is_Ogee
190.05,143.25,2.6,0, 26, 26, , , 0.98, 0, 0,0,,
 3730.66 3730.66 6240.82 6240.82 7722.53 7722.53 8022.53 8022.53   10130   10130
   10880   10880   13860   13860   14610   1461016646.1716646.17   17430 18161.5
 18161.519004.6219004.6219244.62   2000020126.23
     175     175     176     157     159     159   157.9   157.9   159.1   159.1
   159.6   159.6   161.6   161.6   161.6   161.6  164.11  164.11   168.5  165.14
  165.14   161.8   161.8   162.2   163.7   163.7
             171     172                   156.6   155.5                   156.9
   157.4                   157.3   157.3   157.3          157.11     160   157.5
                   159.6   160.1   157.1
 3730.66 3730.66 6240.82 6240.82 7722.53 7722.53 8022.53 8022.53   10130   10130
   10880   10880   13860   13860   14610   1461016646.1716646.17   17430 18161.5
 18161.519004.6219004.6219244.62   2000020126.23
     175     175     176     157     159     159   157.9   157.9   159.1   159.1
   159.6   159.6   161.6   161.6   161.6   161.6  164.11  164.11   168.5  165.14
  165.14   161.8   161.8   162.2   163.7   163.7
             171     172                   156.6   155.5                   156.9
   157.4                   157.3   157.3   157.3          157.11     160   157.5
                   159.6   160.1   157.1
Pier Skew, UpSta & Num, DnSta & Num=  ,7752.53, 2 ,7752.53, 2 , 0 , 0 , 0 ,,
     1.3     1.3
     120     162
     1.3     1.3
     120     162
Pier Skew, UpSta & Num, DnSta & Num=  ,7782.53, 2 ,7782.53, 2 , 0 , 0 , 0 ,,
     1.3     1.3
     120     162
     1.3     1.3
     120     162
Pier Skew, UpSta & Num, DnSta & Num=  ,7812.53, 2 ,7812.53, 2 , 0 , 0 , 0 ,,
     1.3     1.3
     120     162
     1.3     1.3
     120     162
Pier Skew, UpSta & Num, DnSta & Num=  ,7842.53, 2 ,7842.53, 2 , 0 , 0 , 0 ,,
     1.3     1.3
     120     162
     1.3     1.3
     120     162
Pier Skew, UpSta & Num, DnSta & Num=  ,7872.53, 2 ,7872.53, 2 , 0 , 0 , 0 ,,
     1.3     1.3
     120     162
     1.3     1.3
     120     162
Pier Skew, UpSta & Num, DnSta & Num=  ,7902.53, 2 ,7902.53, 2 , 0 , 0 , 0 ,,
     1.3     1.3
     120     162
     1.3     1.3
     120     162
Pier Skew, UpSta & Num, DnSta & Num=  ,7932.53, 2 ,7932.53, 2 , 0 , 0 , 0 ,,
     1.3     1.3
     120     162
     1.3     1.3
     120     162
Pier Skew, UpSta & Num, DnSta & Num=  ,7962.53, 2 ,7962.53, 2 , 0 , 0 , 0 ,,
     1.3     1.3
     120     162
     1.3     1.3
     120     162
Pier Skew, UpSta & Num, DnSta & Num=  ,7992.53, 2 ,7992.53, 2 , 0 , 0 , 0 ,,
     1.3     1.3
     120     162
     1.3     1.3
     120     162
Pier Skew, UpSta & Num, DnSta & Num=  ,10160, 2 ,10160, 2 , 0 , 0 , 0 ,,
     1.3     1.3
     120     162
     1.3     1.3
     120     162
Pier Skew, UpSta & Num, DnSta & Num=  ,10190, 2 ,10190, 2 , 0 , 0 , 0 ,,
     1.3     1.3
     120     162
     1.3     1.3
     120     162
Pier Skew, UpSta & Num, DnSta & Num=  ,10220, 2 ,10220, 2 , 0 , 0 , 0 ,,
     1.3     1.3
     120     162
     1.3     1.3
     120     162
Pier Skew, UpSta & Num, DnSta & Num=  ,10250, 2 ,10250, 2 , 0 , 0 , 0 ,,
     1.3     1.3
     120     162
     1.3     1.3
     120     162
Pier Skew, UpSta & Num, DnSta & Num=  ,10280, 2 ,10280, 2 , 0 , 0 , 0 ,,
     1.3     1.3
     120     162
     1.3     1.3
     120     162
Pier Skew, UpSta & Num, DnSta & Num=  ,10310, 2 ,10310, 2 , 0 , 0 , 0 ,,
     1.3     1.3
     120     162
     1.3     1.3
     120     162
Pier Skew, UpSta & Num, DnSta & Num=  ,10340, 2 ,10340, 2 , 0 , 0 , 0 ,,
     1.3     1.3
     120     162
     1.3     1.3
     120     162
Pier Skew, UpSta & Num, DnSta & Num=  ,10370, 2 ,10370, 2 , 0 , 0 , 0 ,,
     1.3     1.3
     120     162
     1.3     1.3
     120     162
Pier Skew, UpSta & Num, DnSta & Num=  ,10400, 2 ,10400, 2 , 0 , 0 , 0 ,,
     1.3     1.3
     120     162
     1.3     1.3
     120     162
Pier Skew, UpSta & Num, DnSta & Num=  ,10430, 2 ,10430, 2 , 0 , 0 , 0 ,,
     1.3     1.3
     120     162
     1.3     1.3
     120     162
Pier Skew, UpSta & Num, DnSta & Num=  ,10460, 2 ,10460, 2 , 0 , 0 , 0 ,,
     1.3     1.3
     120     162
     1.3     1.3
     120     162
Pier Skew, UpSta & Num, DnSta & Num=  ,10490, 2 ,10490, 2 , 0 , 0 , 0 ,,
       5       5
     120     162
       5       5
     120     162
Pier Skew, UpSta & Num, DnSta & Num=  ,10520, 2 ,10520, 2 , 0 , 0 , 0 ,,
     1.3     1.3
     120     162
     1.3     1.3
     120     162
Pier Skew, UpSta & Num, DnSta & Num=  ,10550, 2 ,10550, 2 , 0 , 0 , 0 ,,
     1.3     1.3
     120     162
     1.3     1.3
     120     162
Pier Skew, UpSta & Num, DnSta & Num=  ,10580, 2 ,10580, 2 , 0 , 0 , 0 ,,
     1.3     1.3
     120     162
     1.3     1.3
     120     162
Pier Skew, UpSta & Num, DnSta & Num=  ,10610, 2 ,10610, 2 , 0 , 0 , 0 ,,
     1.3     1.3
     120     162
     1.3     1.3
     120     162
Pier Skew, UpSta & Num, DnSta & Num=  ,10640, 2 ,10640, 2 , 0 , 0 , 0 ,,
     1.3     1.3
     120     162
     1.3     1.3
     120     162
Pier Skew, UpSta & Num, DnSta & Num=  ,10670, 2 ,10670, 2 , 0 , 0 , 0 ,,
     1.3     1.3
     120     162
     1.3     1.3
     120     162
Pier Skew, UpSta & Num, DnSta & Num=  ,10700, 2 ,10700, 2 , 0 , 0 , 0 ,,
     1.3     1.3
     120     162
     1.3     1.3
     120     162
Pier Skew, UpSta & Num, DnSta & Num=  ,10730, 2 ,10730, 2 , 0 , 0 , 0 ,,
     1.3     1.3
     120     162
     1.3     1.3
     120     162
Pier Skew, UpSta & Num, DnSta & Num=  ,10760, 2 ,10760, 2 , 0 , 0 , 0 ,,
     1.3     1.3
     120     162
     1.3     1.3
     120     162
Pier Skew, UpSta & Num, DnSta & Num=  ,10790, 2 ,10790, 2 , 0 , 0 , 0 ,,
     1.3     1.3
     120     162
     1.3     1.3
     120     162
Pier Skew, UpSta & Num, DnSta & Num=  ,10820, 2 ,10820, 2 , 0 , 0 , 0 ,,
     1.3     1.3
     120     162
     1.3     1.3
     120     162
Pier Skew, UpSta & Num, DnSta & Num=  ,10850, 2 ,10850, 2 , 0 , 0 , 0 ,,
     1.3     1.3
     120     162
     1.3     1.3
     120     162
Pier Skew, UpSta & Num, DnSta & Num=  ,13890, 2 ,13890, 2 , 0 , 0 , 0 ,,
     1.3     1.3
     120     162
     1.3     1.3
     120     162
Pier Skew, UpSta & Num, DnSta & Num=  ,13920, 2 ,13920, 2 , 0 , 0 , 0 ,,
     1.3     1.3
     120     162
     1.3     1.3
     120     162
Pier Skew, UpSta & Num, DnSta & Num=  ,13950, 2 ,13950, 2 , 0 , 0 , 0 ,,
     1.3     1.3
     120     162
     1.3     1.3
     120     162
Pier Skew, UpSta & Num, DnSta & Num=  ,13980, 2 ,13980, 2 , 0 , 0 , 0 ,,
     1.3     1.3
     120     162
     1.3     1.3
     120     162
Pier Skew, UpSta & Num, DnSta & Num=  ,14010, 2 ,14010, 2 , 0 , 0 , 0 ,,
     1.3     1.3
     120     162
     1.3     1.3
     120     162
Pier Skew, UpSta & Num, DnSta & Num=  ,14040, 2 ,14040, 2 , 0 , 0 , 0 ,,
     1.3     1.3
     120     162
     1.3     1.3
     120     162
Pier Skew, UpSta & Num, DnSta & Num=  ,14070, 2 ,14070, 2 , 0 , 0 , 0 ,,
     1.3     1.3
     120     162
     1.3     1.3
     120     162
Pier Skew, UpSta & Num, DnSta & Num=  ,14100, 2 ,14100, 2 , 0 , 0 , 0 ,,
     1.3     1.3
     120     162
     1.3     1.3
     120     162
Pier Skew, UpSta & Num, DnSta & Num=  ,14130, 2 ,14130, 2 , 0 , 0 , 0 ,,
     1.3     1.3
     120     162
     1.3     1.3
     120     162
Pier Skew, UpSta & Num, DnSta & Num=  ,14160, 2 ,14160, 2 , 0 , 0 , 0 ,,
     1.3     1.3
     120     162
     1.3     1.3
     120     162
Pier Skew, UpSta & Num, DnSta & Num=  ,14190, 2 ,14190, 2 , 0 , 0 , 0 ,,
     1.3     1.3
     120     162
     1.3     1.3
     120     162
Pier Skew, UpSta & Num, DnSta & Num=  ,14220, 2 ,14220, 2 , 0 , 0 , 0 ,,
     1.3     1.3
     120     162
     1.3     1.3
     120     162
Pier Skew, UpSta & Num, DnSta & Num=  ,14250, 2 ,14250, 2 , 0 , 0 , 0 ,,
       5       5
     120     162
       5       5
     120     162
Pier Skew, UpSta & Num, DnSta & Num=  ,14280, 2 ,14280, 2 , 0 , 0 , 0 ,,
     1.3     1.3
     120     162
     1.3     1.3
     120     162
Pier Skew, UpSta & Num, DnSta & Num=  ,14310, 2 ,14310, 2 , 0 , 0 , 0 ,,
     1.3     1.3
     120     162
     1.3     1.3
     120     162
Pier Skew, UpSta & Num, DnSta & Num=  ,14340, 2 ,14340, 2 , 0 , 0 , 0 ,,
     1.3     1.3
     120     162
     1.3     1.3
     120     162
Pier Skew, UpSta & Num, DnSta & Num=  ,14370, 2 ,14370, 2 , 0 , 0 , 0 ,,
     1.3     1.3
     120     162
     1.3     1.3
     120     162
Pier Skew, UpSta & Num, DnSta & Num=  ,14400, 2 ,14400, 2 , 0 , 0 , 0 ,,
     1.3     1.3
     120     162
     1.3     1.3
     120     162
Pier Skew, UpSta & Num, DnSta & Num=  ,14430, 2 ,14430, 2 , 0 , 0 , 0 ,,
     1.3     1.3
     120     162
     1.3     1.3
     120     162
Pier Skew, UpSta & Num, DnSta & Num=  ,14460, 2 ,14460, 2 , 0 , 0 , 0 ,,
     1.3     1.3
     120     162
     1.3     1.3
     120     162
Pier Skew, UpSta & Num, DnSta & Num=  ,14490, 2 ,14490, 2 , 0 , 0 , 0 ,,
     1.3     1.3
     120     162
     1.3     1.3
     120     162
Pier Skew, UpSta & Num, DnSta & Num=  ,14520, 2 ,14520, 2 , 0 , 0 , 0 ,,
     1.3     1.3
     120     162
     1.3     1.3
     120     162
Pier Skew, UpSta & Num, DnSta & Num=  ,14550, 2 ,14550, 2 , 0 , 0 , 0 ,,
     1.3     1.3
     120     162
     1.3     1.3
     120     162
Pier Skew, UpSta & Num, DnSta & Num=  ,14580, 2 ,14580, 2 , 0 , 0 , 0 ,,
     1.3     1.3
     120     162
     1.3     1.3
     120     162
Pier Skew, UpSta & Num, DnSta & Num=  ,16761.33, 4 ,16761.33, 4 , 0 , 0 , 0 ,,
       5       5       4       4
     120     129     129     162
       5       5       4       4
     120     129     129     162
Pier Skew, UpSta & Num, DnSta & Num=  ,16876.33, 4 ,16876.33, 4 , 0 , 0 , 0 ,,
       5       5       4       4
     120     129     129     162
       5       5       4       4
     120     129     129     162
Pier Skew, UpSta & Num, DnSta & Num=  ,17012.17, 4 ,17012.17, 4 , 0 , 0 , 0 ,,
       5       5       4       4
     120     129     129     162
       5       5       4       4
     120     129     129     162
Pier Skew, UpSta & Num, DnSta & Num=  ,17148, 4 ,17148, 4 , 0 , 0 , 0 ,,
       5       5       4       4
     120     129     129     162
       5       5       4       4
     120     129     129     162
Pier Skew, UpSta & Num, DnSta & Num=  ,17283.83, 2 ,17283.83, 2 , 0 , 0 , 0 ,,
       4       4
     120     162
       4       4
     120     162
Pier Skew, UpSta & Num, DnSta & Num=  ,17440.58, 2 ,17440.58, 2 , 0 , 0 , 0 ,,
       4       4
     120     162
       4       4
     120     162
Pier Skew, UpSta & Num, DnSta & Num=  ,17597.33, 2 ,17597.33, 2 , 0 , 0 , 0 ,,
       4       4
     120     162
       4       4
     120     162
Pier Skew, UpSta & Num, DnSta & Num=  ,17754.08, 4 ,17754.08, 4 , 0 , 0 , 0 ,,
       5       5       4       4
     120     129     129     162
       5       5       4       4
     120     129     129     162
Pier Skew, UpSta & Num, DnSta & Num=  ,17889.92, 4 ,17889.92, 4 , 0 , 0 , 0 ,,
       5       5       4       4
     120     129     129     162
       5       5       4       4
     120     129     129     162
Pier Skew, UpSta & Num, DnSta & Num=  ,18025.75, 4 ,18025.75, 4 , 0 , 0 , 0 ,,
       5       5       4       4
     120     129     129     162
       5       5       4       4
     120     129     129     162
Pier Skew, UpSta & Num, DnSta & Num=  ,19034.62, 2 ,19034.62, 2 , 0 , 0 , 0 ,,
     1.3     1.3
     120     162
     1.3     1.3
     120     162
Pier Skew, UpSta & Num, DnSta & Num=  ,19064.62, 2 ,19064.62, 2 , 0 , 0 , 0 ,,
     1.3     1.3
     120     162
     1.3     1.3
     120     162
Pier Skew, UpSta & Num, DnSta & Num=  ,19094.62, 2 ,19094.62, 2 , 0 , 0 , 0 ,,
     1.3     1.3
     120     162
     1.3     1.3
     120     162
Pier Skew, UpSta & Num, DnSta & Num=  ,19124.62, 2 ,19124.62, 2 , 0 , 0 , 0 ,,
     1.3     1.3
     120     162
     1.3     1.3
     120     162
Pier Skew, UpSta & Num, DnSta & Num=  ,19154.62, 2 ,19154.62, 2 , 0 , 0 , 0 ,,
     1.3     1.3
     120     162
     1.3     1.3
     120     162
Pier Skew, UpSta & Num, DnSta & Num=  ,19184.62, 2 ,19184.62, 2 , 0 , 0 , 0 ,,
     1.3     1.3
     120     162
     1.3     1.3
     120     162
Pier Skew, UpSta & Num, DnSta & Num=  ,19214.62, 2 ,19214.62, 2 , 0 , 0 , 0 ,,
     1.3     1.3
     120     162
     1.3     1.3
     120     162
BR Coef=-1 , 1 , 0 ,, 0 ,,,0.8,-1,2,0,
WSPro=,,,, 1 ,,,, 0 ,,,, 0 ,,,,-1 ,-1 ,-1 , 0 , 0 , 0 , 0 , 0
BC Mult= 3 ,-200,9000,-200,9000
BC Mult= 3 ,8500,12500,8500,12500
BC Mult= 3 ,12000,16000,12000,16000
BC Mult= 3 ,15500,19000,15500,19000
BC Mult= 3 ,18500,23000,18500,23000
BR U #Sta/Elev= 30
       0 164.0063730.661 176.599 3871.92 146.838 3962.73 179.375 5933.39 175.911
6003.947 153.6976170.261 153.8536240.819 175.3017717.487 156.8587838.443 126.696
8024.917 157.196 10111.6 159.05510257.82 136.10810802.68 138.29710872.98 157.143
13737.38 159.131 13917.6   136.5 14343.6  134.9614559.11 138.49414614.24 160.531
16607.68  160.4217225.88 134.77917492.77 110.52817717.63 130.79118177.96 161.345
19004.62 161.633 19050.7   136.219201.37   136.219248.12 162.45220126.23 163.047
BR U #Mann= 3
       0     .0617225.88     .0517717.63     .06
BR U Banks=17225.88,17717.63
BR D #Sta/Elev= 30
       0 164.0063730.661 176.599 3871.92 146.838 3962.73 179.375 5933.39 175.911
6003.947 153.6976170.261 153.8536240.819 175.3017717.487 156.8587838.443 126.696
8024.917 157.196 10111.6 159.05510257.82 136.10810802.68 138.29710872.98 157.143
13737.38 159.131 13917.6   136.5 14343.6  134.9614559.11 138.49414614.24 160.531
16607.68  160.4217225.88 134.77917492.77 110.52817717.63 130.79118177.96 161.345
19004.62 161.633 19050.7   136.219201.37   136.219248.12 162.45220126.23 163.047
BR D #Mann= 3
       0     .0617225.88     .0517717.63     .06
BR D Banks=17225.88,17717.63
BC Design=,, 0 ,, 0 ,,,,,,
BC Use User HTab Curves=0
BC User HTab FreeFlow(D)= 0

Type RM Length L Ch R = 1 ,347864  ,4350,9194,3000
#Sta/Elev= 30
  -115.2  163.92   906.9  167.46  1607.8  152.32  3443.2     140  3750.7  144.06
    3776  152.37  5984.5  150.88  7613.1  140.98  7794.6  126.19    7956  140.72
 11596.5  133.07 12519.2   141.2   13331  133.07 15157.7  147.75 16951.9  139.02
 17025.8  129.12 17092.7   137.6 17364.4  132.47 17398.8  117.84   17500  110.78
 17703.2   114.6 17781.3  134.48 17983.1  145.11 19065.3  135.15 19132.8  151.57
 19679.5  156.11 19757.1   137.6 19918.4   144.8 20147.3  135.8121928.36  166.55
#Mann= 3 , 0 , 0
  -115.2     .09       0 16951.9    .045       0 17781.3     .09       0
Bank Sta=16951.9,17781.3
XS Rating Curve= 0 ,0
Exp/Cntr(USF)=0,0
Exp/Cntr=0.5,0.3

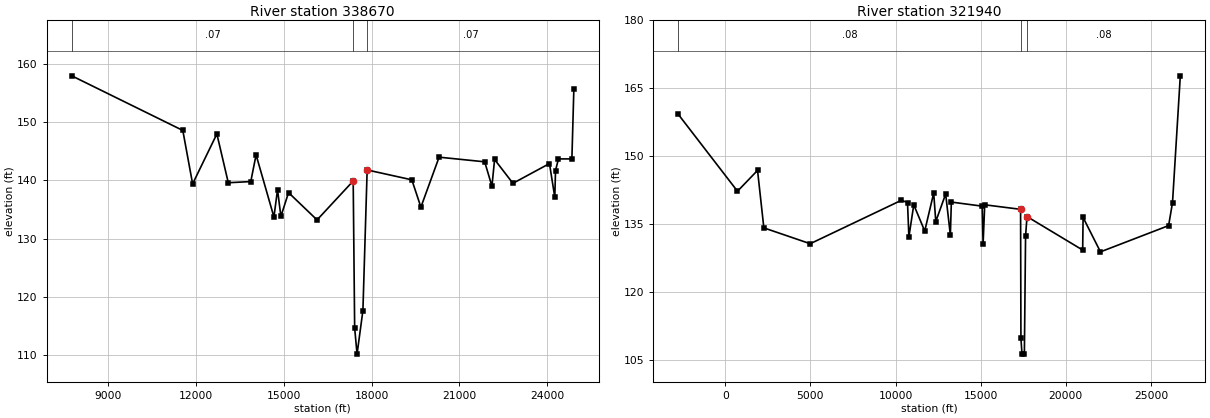
Type RM Length L Ch R = 1 ,338670  ,4300,16730,6500
BEGIN DESCRIPTION:
LETTERED D
END DESCRIPTION:
#Sta/Elev= 30
    7750     158   11545   148.6   11880   139.4   12709     148   13099   139.6
   13868   139.8   14049   144.4   14659   133.7   14782   138.4   14897   133.8
   15158   137.9   16133   133.2   17368   139.9   17418   114.6   17500   110.1
   17700   117.6   17845   141.8   19372   140.1   19682   135.4   20304     144
   21862   143.2   22110     139   22200   143.6   22827   139.5   24076   142.9
   24258   137.1   24283   141.7   24383   143.7   24842   143.7   24909   155.7
#Mann= 3 , 0 , 0
    7750     .07       0   17368    .045       0   17845     .07       0
Bank Sta=17368,17845
XS Rating Curve= 0 ,0
Exp/Cntr=0.3,0.1

Type RM Length L Ch R = 1 ,321940  ,5700,15660,4400
BEGIN DESCRIPTION:
LETTERED C
END DESCRIPTION:
#Sta/Elev= 30
   -2764   159.2     716   142.2    1894   146.8    2264   134.1    4987   130.6
   10345   140.2   10702   139.7   10783   132.1   11070   139.2   11713   133.4
   12240   141.8   12363   135.5   12943   141.6   13219   132.5   13277   139.8
   15088   138.9   15141   130.5   15237   139.2   17343   138.2   17364   109.7
   17426   106.2   17566   106.2   17636   132.2   17720   136.6   20990   129.2
   21015   136.4   22035   128.8   26038   134.6   26267   139.7   26725   167.7
#Mann= 3 , 0 , 0
   -2764     .08       0   17343    .045       0   17720     .08       0
Bank Sta=17343,17720
XS Rating Curve= 0 ,0
Exp/Cntr=0.3,0.1
LCMann Table=0

Chan Stop Cuts=-1
Use User Specified Reach Order=0
Composite Channel Slope=5

--- Wateree_River.g03 (geometry) ---

Geom Title=HEC2_working
Program Version=5.07

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
River Reach=River 1         ,Reach 1

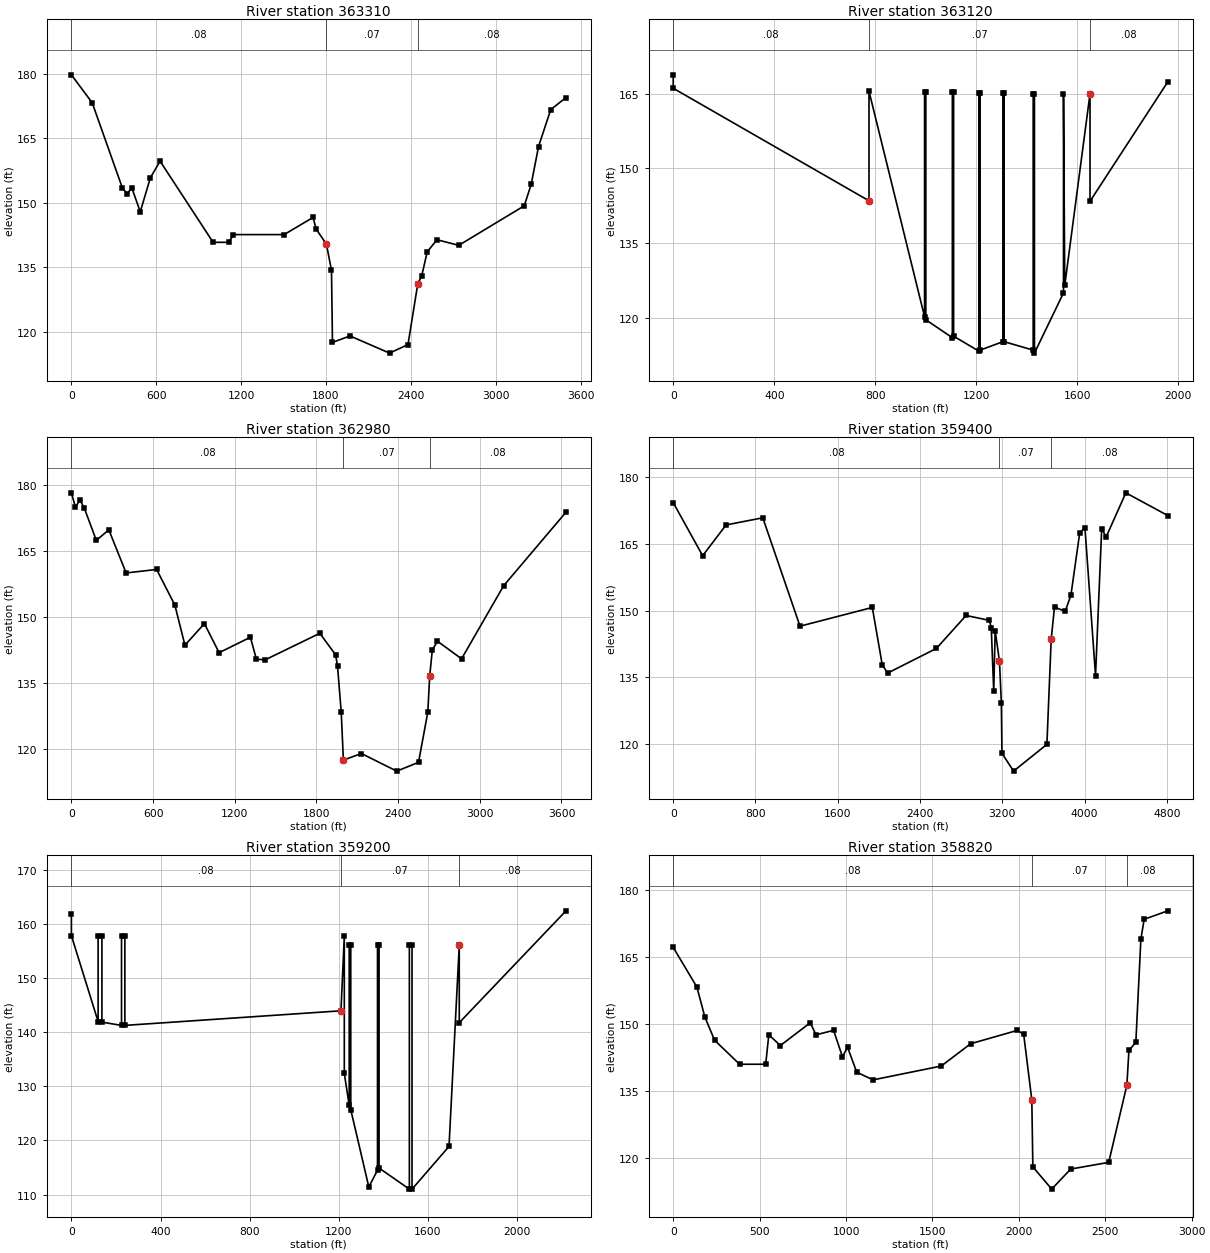
Type RM Length L Ch R = 1 ,363310  ,190,190,190
#Sta/Elev= 30
       0   179.8     147   173.3     360   153.5     394   152.1     427   153.5
     487   147.9     558   155.8     627   159.7    1002   140.8    1113   140.8
    1146   142.6    1504   142.6    1709   146.6    1730   143.9    1803   140.4
    1839   134.3    1846   117.5    1970     119    2250     115    2380     117
    2449   131.1    2477     133    2516   138.6    2585   141.4    2739   140.1
    3202   149.3    3251   154.3    3303   163.1    3389   171.7    3497   174.5
#Mann= 3 , 0 , 0
       0     .08       0    1803     .07       0    2449     .08       0
Bank Sta=1803,2449
XS Rating Curve= 0 ,0
Exp/Cntr=0.3,0.1

Type RM Length L Ch R = 1 ,363120  ,140,140,140
#Sta/Elev= 30
       0   168.8       0   166.1     775   143.5     775   165.5     995   120.2
     995   165.4    1000   165.4    1000   119.6    1105     116    1105   165.3
    1110   165.3    1110   116.3    1210   113.3    1210   165.2    1215   165.2
    1215   113.5    1305   115.2    1305   165.1    1310   165.1    1310   115.2
    1425   113.5    1425     165    1430     165    1430   112.9    1545     125
    1545     165    1550   126.5    1650     165    1650   143.4    1958   167.4
#Mann= 3 , 0 , 0
       0     .08       0     775     .07       0    1650     .08       0
Bank Sta=775,1650
XS Rating Curve= 0 ,0
Exp/Cntr=0.3,0.1

Type RM Length L Ch R = 1 ,362980  ,3500,3580,3530
#Sta/Elev= 30
       0   178.2      30   174.9      62   176.6      94   174.8     183   167.4
     275   169.8     402     160     626   160.8     760   152.7     834   143.6
     977   148.5    1085   141.9    1315   145.4    1359   140.4    1425   140.3
    1825   146.3    1941   141.4    1955   138.8    1982   128.4    1998   117.5
    2130     119    2390     115    2550     117    2618   128.4    2632   136.6
    2651   142.5    2689   144.5    2866   140.5    3175   157.1    3633   173.8
#Mann= 3 , 0 , 0
       0     .08       0    1998     .07       0    2632     .08       0
Bank Sta=1998,2632
XS Rating Curve= 0 ,0
Exp/Cntr=0.3,0.1

Type RM Length L Ch R = 1 ,359400  ,270,200,170
#Sta/Elev= 30
       0   174.2     286   162.3     514   169.2     871   170.8    1233   146.5
    1936   150.7    2033   137.8    2086     136    2559   141.5    2848   148.9
    3075   147.8    3093   146.1    3117   131.9    3131   145.5    3173   138.6
    3191   129.3    3197     118    3310     114    3634     120    3676   143.6
    3708   150.8    3812   149.8    3868   153.5    3953   167.4    4004   168.6
    4107   135.4    4167   168.4    4210   166.5    4402   176.4    4810   171.3
#Mann= 3 , 0 , 0
       0     .08       0    3173     .07       0    3676     .08       0
Bank Sta=3173,3676
XS Rating Curve= 0 ,0
Exp/Cntr=0.3,0.1

Type RM Length L Ch R = 1 ,359200  ,250,380,400
#Sta/Elev= 30
       0   161.9       0   157.9     120     142     120   157.9     137   157.9
     137   141.9     225   141.3     225   157.9     240   157.9     240   141.3
    1210     144    1225   157.8    1225   132.4    1247   126.5    1247   156.1
    1254   156.1    1254   125.7    1335   111.4    1374   114.5    1374   156.1
    1381   156.1    1381   114.9    1517     111    1517   156.1    1529   156.1
    1529     111    1695   118.9    1741   156.1    1741   141.8    2220   162.5
#Mann= 3 , 0 , 0
       0     .08       0    1210     .07       0    1741     .08       0
Bank Sta=1210,1741
XS Rating Curve= 0 ,0
Exp/Cntr=0.3,0.1

Type RM Length L Ch R = 1 ,358820  ,1800,2170,2200
BEGIN DESCRIPTION:
LETTERED F
END DESCRIPTION:
#Sta/Elev= 30
       0   167.2     137   158.3     183   151.6     239   146.4     384     141
     535     141     553   147.6     620   145.2     793   150.3     826   147.6
     928   148.6     979   142.7    1009   144.8    1062   139.2    1157   137.5
    1551   140.6    1721   145.6    1992   148.6    2028   147.7    2075     133
    2081     118    2190     113    2300   117.5    2520     119    2625   136.3
    2637   144.1    2677   145.9    2706     169    2725   173.5    2862   175.4
#Mann= 3 , 0 , 0
       0     .08       0    2075     .07       0    2625     .08       0
Bank Sta=2075,2625
XS Rating Curve= 0 ,0
Exp/Cntr=0.3,0.1