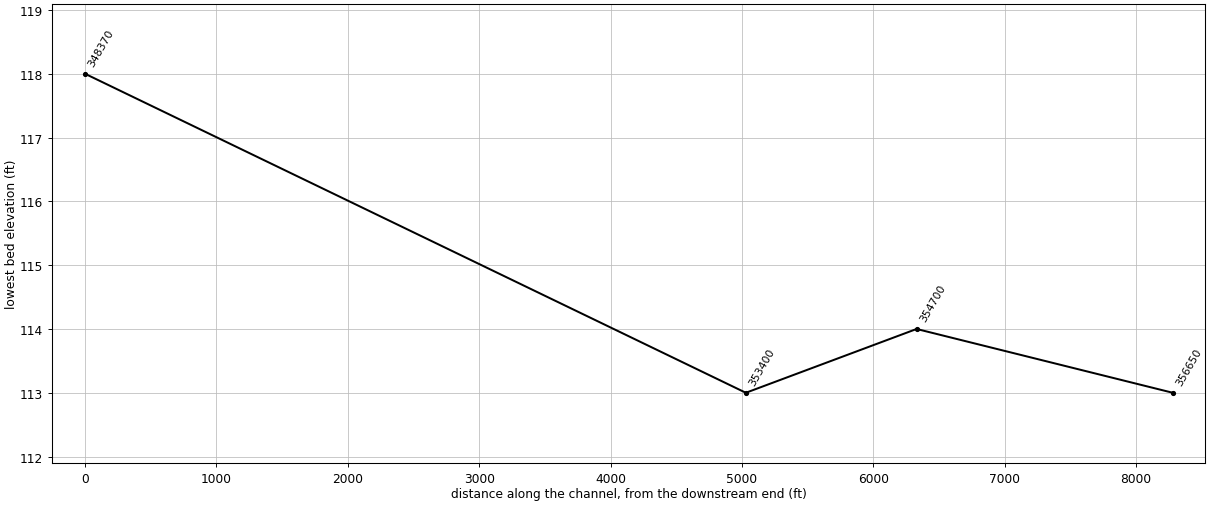
HEC-RAS study Wateree_River.prj: Wateree_River

--- Wateree_River.g03 (geometry) --- (continued)

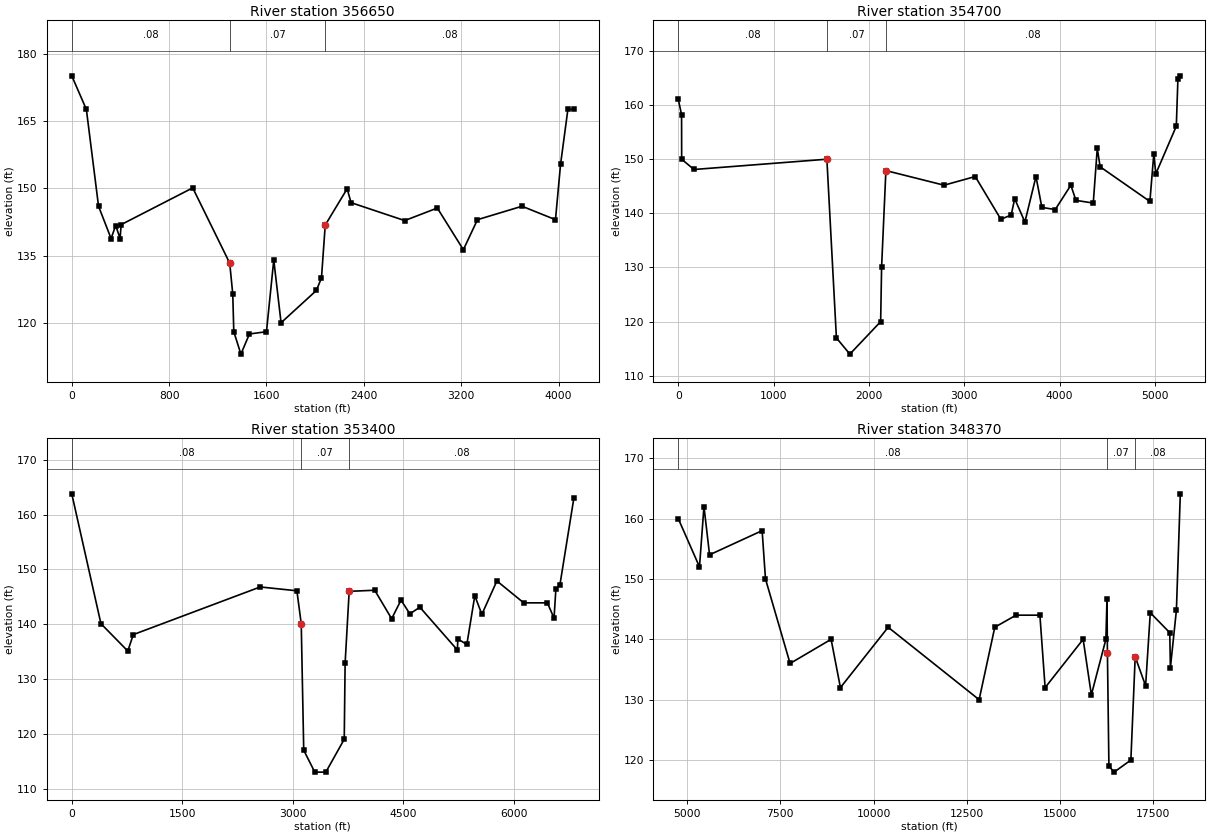
Type RM Length L Ch R = 1 ,356650  ,2400,1950,1200
#Sta/Elev= 30
       0   175.1     120   167.6     220     146     323   138.8     361   141.7
     397   138.8     406   141.9     994   150.1    1298   133.3    1323   126.4
  1331.5     118    1390     113    1460   117.5    1600     118    1660     134
    1720     120    2010   127.2    2052     130    2083   141.8    2263   149.9
    2295   146.8    2736   142.8    3004   145.6    3218   136.3    3334     143
    3700     146    3975     143    4017   155.4    4077   167.6    4126   167.6
#Mann= 3 , 0 , 0
       0     .08       0    1298     .07       0    2083     .08       0
Bank Sta=1298,2083
XS Rating Curve= 0 ,0
Exp/Cntr=0.3,0.1

Type RM Length L Ch R = 1 ,354700  ,1500,1300,1000
#Sta/Elev= 30
       0   161.1      35   158.2      36     150     165   148.1    1559     150
    1659     117    1800     114    2123     120    2133   130.1    2178   147.9
    2788   145.2    3115   146.8    3384   138.9    3492   139.7    3529   142.7
    3636   138.4    3752   146.8    3814   141.1    3954   140.7    4118   145.2
    4171   142.4    4353   141.9    4395     152    4425   148.6    4947   142.2
    4988     151    5009   147.3    5224   156.1    5241   164.9    5266   165.4
#Mann= 3 , 0 , 0
       0     .08       0    1559     .07       0    2178     .08       0
Bank Sta=1559,2178
XS Rating Curve= 0 ,0
Exp/Cntr=0.3,0.1

Type RM Length L Ch R = 1 ,353400  ,5300,5030,4000
BEGIN DESCRIPTION:
LETTERED E
END DESCRIPTION:
#Sta/Elev= 30
       0   163.8     396   140.1     761   135.1     835   138.1    2559   146.8
    3057   146.1    3116   140.1    3150     117    3300     113    3450     113
    3700     119    3712   132.9    3767     146    4114   146.2    4344     141
    4471   144.4    4591   141.9    4727   143.1    5236   135.3    5243   137.3
    5365   136.3    5473   145.2    5569   141.8    5773   147.9    6137   143.9
    6459   143.9    6549   141.1    6574   146.4    6629   147.2    6818     163
#Mann= 3 , 0 , 0
       0     .08       0    3116     .07       0    3767     .08       0
Bank Sta=3116,3767
XS Rating Curve= 0 ,0
Exp/Cntr=0.3,0.1

Type RM Length L Ch R = 1 ,348370  ,150,150,150
#Sta/Elev= 30
    4760     160    5330     152    5450     162    5600     154    7010     158
    7100     150    7760     136    8860     140    9110     132   10390     142
   12830     130   13250     142   13820     144   14460     144   14600     132
   15620     140   15840   130.8   16230     140   16259   146.6   16271   137.8
   16311     119   16450     118   16900     120   17016   137.1   17295   132.3
   17421   144.4   17943   141.1   17960   135.3   18121   144.8   18226   164.1
#Mann= 3 , 0 , 0
    4760     .08       0   16271     .07       0   17016     .08       0
Bank Sta=16271,17016
XS Rating Curve= 0 ,0
Exp/Cntr=0.3,0.1