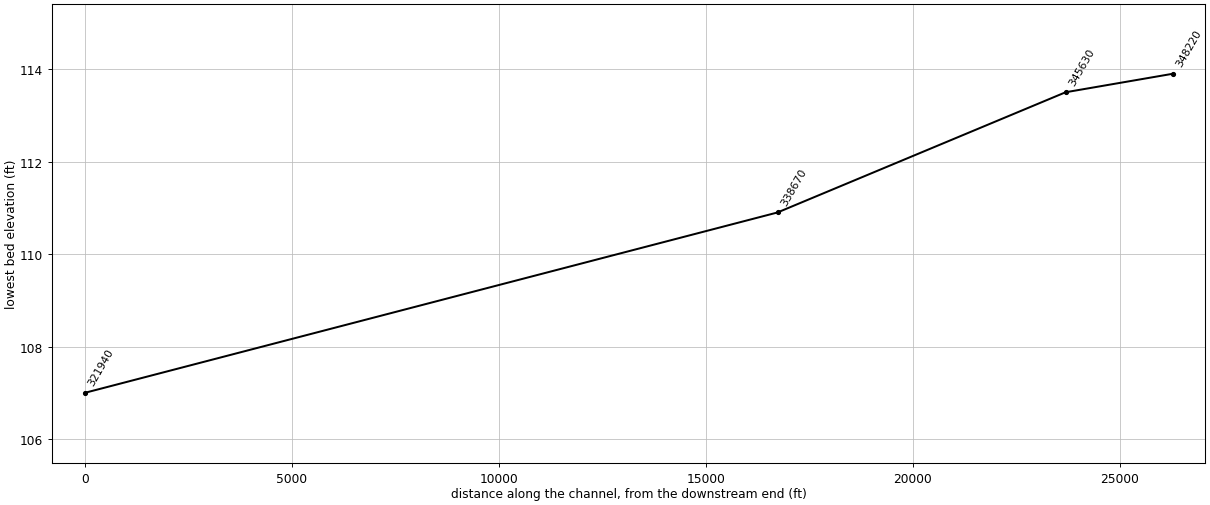
HEC-RAS study Wateree_River.prj: Wateree_River

--- Wateree_River.g03 (geometry) --- (continued)

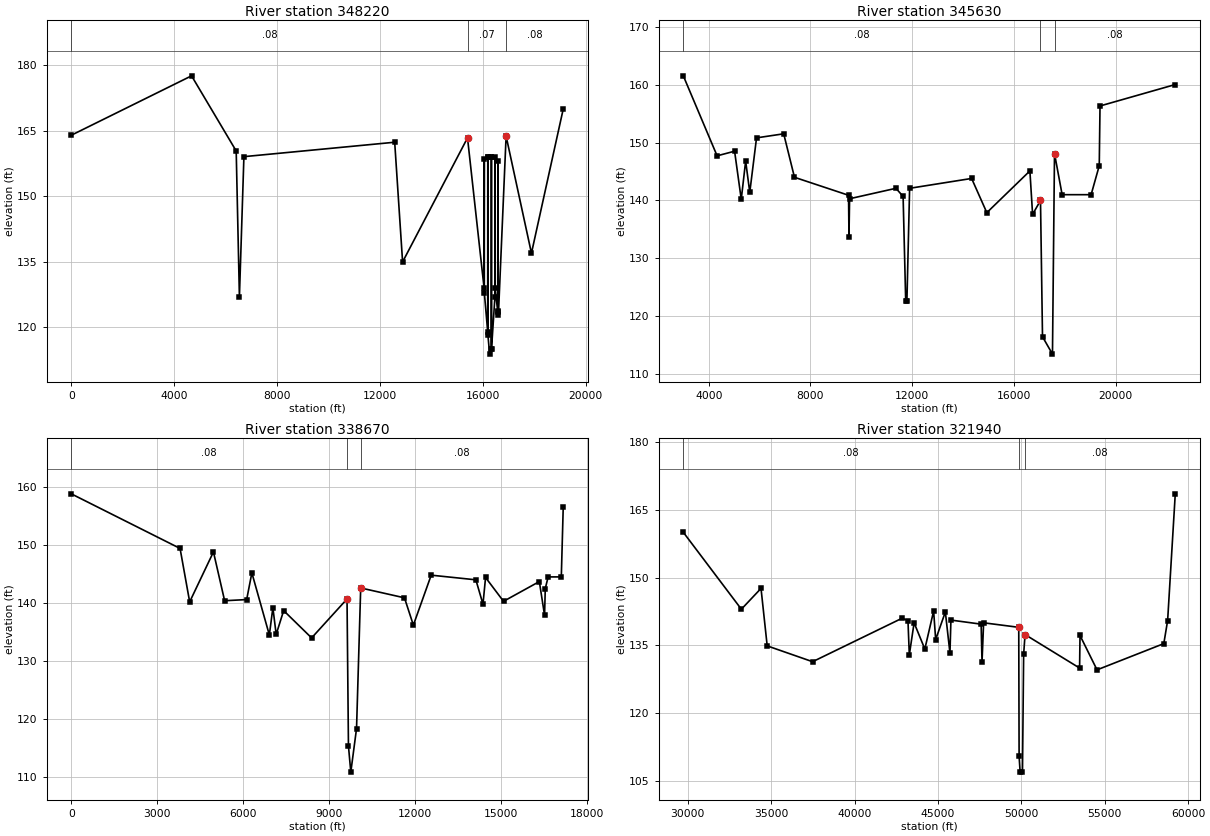
Type RM Length L Ch R = 1 ,348220  ,1400,2590,600
#Sta/Elev= 30
       0     164    4675   177.6    6410   160.4    6535     127    6710   159.1
   12570   162.4   12877     135   15400   163.4   16045     129   16052   158.5
   16053     128   16185     119   16187     159   16192     159   16194   118.2
   16260   113.9   16325     115   16327     159   16331     159   16333   115.1
   16466     127   16467     159   16472     129   16574   123.7   16580   158.2
   16581   123.5   16600   122.8   16900   163.8   17885     137   19120     170
#Mann= 3 , 0 , 0
       0     .08       0   15400     .07       0   16900     .08       0
Bank Sta=15400,16900
XS Rating Curve= 0 ,0
Exp/Cntr=0.3,0.1

Type RM Length L Ch R = 1 ,345630  ,3100,6960,1600
#Sta/Elev= 30
    3000   161.5    4329   147.7    5017   148.5    5279   140.2    5452   146.8
    5614   141.4    5880   150.8    6949   151.5    7372     144    9499   140.9
    9516   133.7    9540   140.3   11363   142.1   11645   140.7   11747   122.7
   11795   122.7   11901   142.1   14340   143.8   14938   137.9   16632   145.1
   16738   137.6   17049     140   17128   116.5   17520   113.5   17600   148.1
   17900     141   19040     141   19360     146   19390   156.3   22350     160
#Mann= 3 , 0 , 0
    3000     .08       0   17049     .07       0   17600     .08       0
Bank Sta=17049,17600
XS Rating Curve= 0 ,0
Exp/Cntr=0.3,0.1

Type RM Length L Ch R = 1 ,338670  ,4300,16730,6500
BEGIN DESCRIPTION:
LETTERD D
END DESCRIPTION:
#Sta/Elev= 30
       0   158.8    3795   149.4    4130   140.2    4959   148.8    5349   140.4
    6118   140.6    6299   145.2    6909   134.5    7032   139.2    7147   134.6
    7408   138.7    8383     134    9618   140.7    9668   115.4    9750   110.9
    9950   118.4   10095   142.6   11622   140.9   11932   136.2   12554   144.8
   14112     144   14360   139.8   14450   144.4   15077   140.3   16326   143.7
   16508   137.9   16533   142.5   16633   144.5   17092   144.5   17159   156.5
#Mann= 3 , 0 , 0
       0     .08       0    9618     .07       0   10095     .08       0
Bank Sta=9618,10095
XS Rating Curve= 0 ,0
Exp/Cntr=0.3,0.1

Type RM Length L Ch R = 1 ,321940  ,5700,15660,4400
BEGIN DESCRIPTION:
SECTION C
END DESCRIPTION:
#Sta/Elev= 30
   29736     160   33216     143   34394   147.6   34764   134.9   37487   131.4
   42845     141   43202   140.5   43283   132.9   43570     140   44213   134.2
   44740   142.6   44863   136.3   45443   142.4   45719   133.3   45777   140.6
   47588   139.7   47641   131.3   47737     140   49843     139   49864   110.5
   49926     107   50066     107   50136     133   50220   137.4   53490     130
   53515   137.2   54535   129.6   58538   135.4   58767   140.5   59225   168.5
#Mann= 3 , 0 , 0
   29736     .08       0   49843     .07       0   50220     .08       0
Bank Sta=49843,50220
XS Rating Curve= 0 ,0
Exp/Cntr=0.3,0.1
LCMann Table=0

--- Wateree_River.g04 (geometry) ---

Geom Title=HEC2_NAVD88
Program Version=5.07

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
River Reach=River 1         ,Reach 1

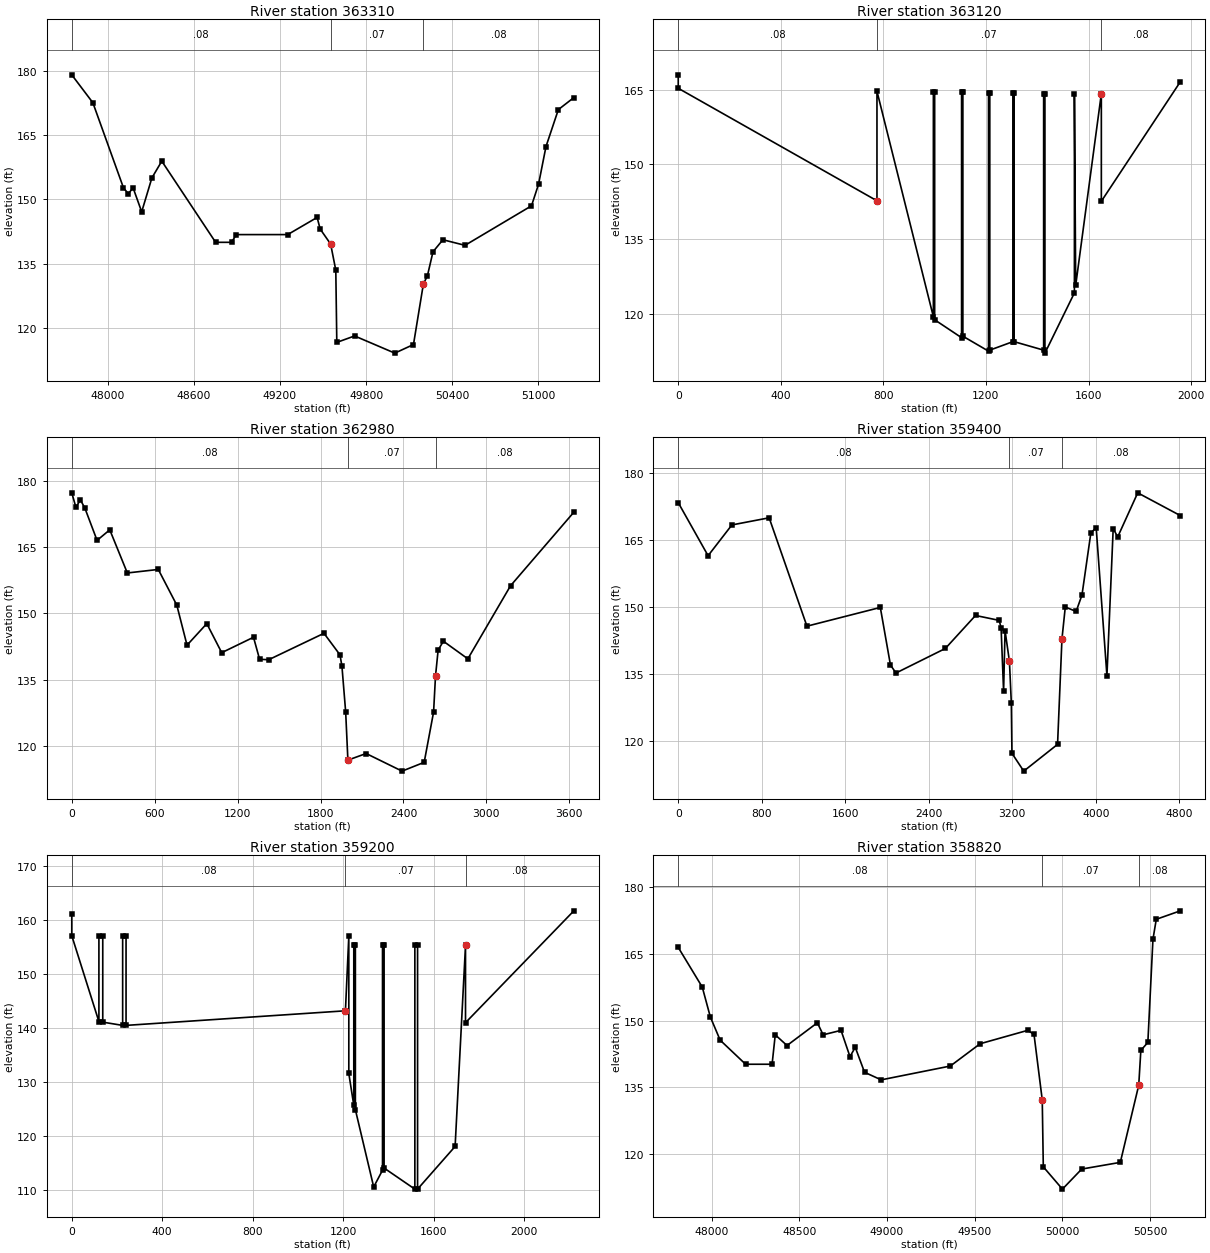
Type RM Length L Ch R = 1 ,363310  ,190,190,190
BEGIN DESCRIPTION:
LETTERED G
END DESCRIPTION:
#Sta/Elev= 30
   47750     179   47897   172.5   48110   152.7   48144   151.3   48177   152.7
   48237   147.1   48308     155   48377   158.9   48752     140   48863     140
   48896   141.8   49254   141.8   49459   145.8   49480   143.1   49553   139.6
   49589   133.5   49596   116.7   49720   118.2   50000   114.2   50130   116.2
   50199   130.3   50227   132.2   50266   137.8   50335   140.6   50489   139.3
   50952   148.5   51001   153.5   51053   162.3   51139   170.9   51247   173.7
#Mann= 3 , 0 , 0
   47750     .08       0   49553     .07       0   50199     .08       0
Bank Sta=49553,50199
XS Rating Curve= 0 ,0
Exp/Cntr=0.3,0.1

Type RM Length L Ch R = 1 ,363120  ,140,140,140
#Sta/Elev= 30
       0     168       0   165.3     775   142.7     775   164.7     995   119.4
     995   164.6    1000   164.6    1000   118.8    1105   115.2    1105   164.5
    1110   164.5    1110   115.5    1210   112.5    1210   164.4    1215   164.4
    1215   112.7    1305   114.4    1305   164.3    1310   164.3    1310   114.4
    1425   112.7    1425   164.2    1430   164.2    1430   112.1    1545   124.2
    1545   164.2    1550   125.7    1650   164.2    1650   142.6    1958   166.6
#Mann= 3 , 0 , 0
       0     .08       0     775     .07       0    1650     .08       0
Bank Sta=775,1650
XS Rating Curve= 0 ,0
Exp/Cntr=0.3,0.1

Type RM Length L Ch R = 1 ,362980  ,3500,3580,3530
#Sta/Elev= 30
       0   177.4      30   174.1      62   175.8      94     174     183   166.6
     275     169     402   159.2     626     160     760   151.9     834   142.8
     977   147.7    1085   141.1    1315   144.6    1359   139.6    1425   139.5
    1825   145.5    1941   140.6    1955     138    1982   127.6    1998   116.7
    2130   118.2    2390   114.2    2550   116.2    2618   127.6    2632   135.8
    2651   141.7    2689   143.7    2866   139.7    3175   156.3    3633     173
#Mann= 3 , 0 , 0
       0     .08       0    1998     .07       0    2632     .08       0
Bank Sta=1998,2632
XS Rating Curve= 0 ,0
Exp/Cntr=0.3,0.1

Type RM Length L Ch R = 1 ,359400  ,270,200,170
#Sta/Elev= 30
       0   173.4     286   161.5     514   168.4     871     170    1233   145.7
    1936   149.9    2033     137    2086   135.2    2559   140.7    2848   148.1
    3075     147    3093   145.3    3117   131.1    3131   144.7    3173   137.8
    3191   128.5    3197   117.2    3310   113.2    3634   119.2    3676   142.8
    3708     150    3812     149    3868   152.7    3953   166.6    4004   167.8
    4107   134.6    4167   167.6    4210   165.7    4402   175.6    4810   170.5
#Mann= 3 , 0 , 0
       0     .08       0    3173     .07       0    3676     .08       0
Bank Sta=3173,3676
XS Rating Curve= 0 ,0
Exp/Cntr=0.3,0.1

Type RM Length L Ch R = 1 ,359200  ,250,380,400
#Sta/Elev= 30
       0   161.1       0   157.1     120   141.2     120   157.1     137   157.1
     137   141.1     225   140.5     225   157.1     240   157.1     240   140.5
    1210   143.2    1225     157    1225   131.6    1247   125.7    1247   155.3
    1254   155.3    1254   124.9    1335   110.6    1374   113.7    1374   155.3
    1381   155.3    1381   114.1    1517   110.2    1517   155.3    1529   155.3
    1529   110.2    1695   118.1    1741   155.3    1741     141    2220   161.7
#Mann= 3 , 0 , 0
       0     .08       0    1210     .07       0    1741     .08       0
Bank Sta=1210,1741
XS Rating Curve= 0 ,0
Exp/Cntr=0.3,0.1

Type RM Length L Ch R = 1 ,358820  ,1800,2170,2200
BEGIN DESCRIPTION:
LETTERED F
END DESCRIPTION:
#Sta/Elev= 30
   47810   166.4   47947   157.5   47993   150.8   48049   145.6   48194   140.2
   48345   140.2   48363   146.8   48430   144.4   48603   149.5   48636   146.8
   48738   147.8   48789   141.9   48819     144   48872   138.4   48967   136.7
   49361   139.8   49531   144.8   49802   147.8   49838   146.9   49885   132.2
   49891   117.2   50000   112.2   50110   116.7   50330   118.2   50435   135.5
   50447   143.3   50487   145.1   50516   168.2   50535   172.7   50672   174.6
#Mann= 3 , 0 , 0
   47810     .08       0   49885     .07       0   50435     .08       0
Bank Sta=49885,50435
XS Rating Curve= 0 ,0
Exp/Cntr=0.3,0.1

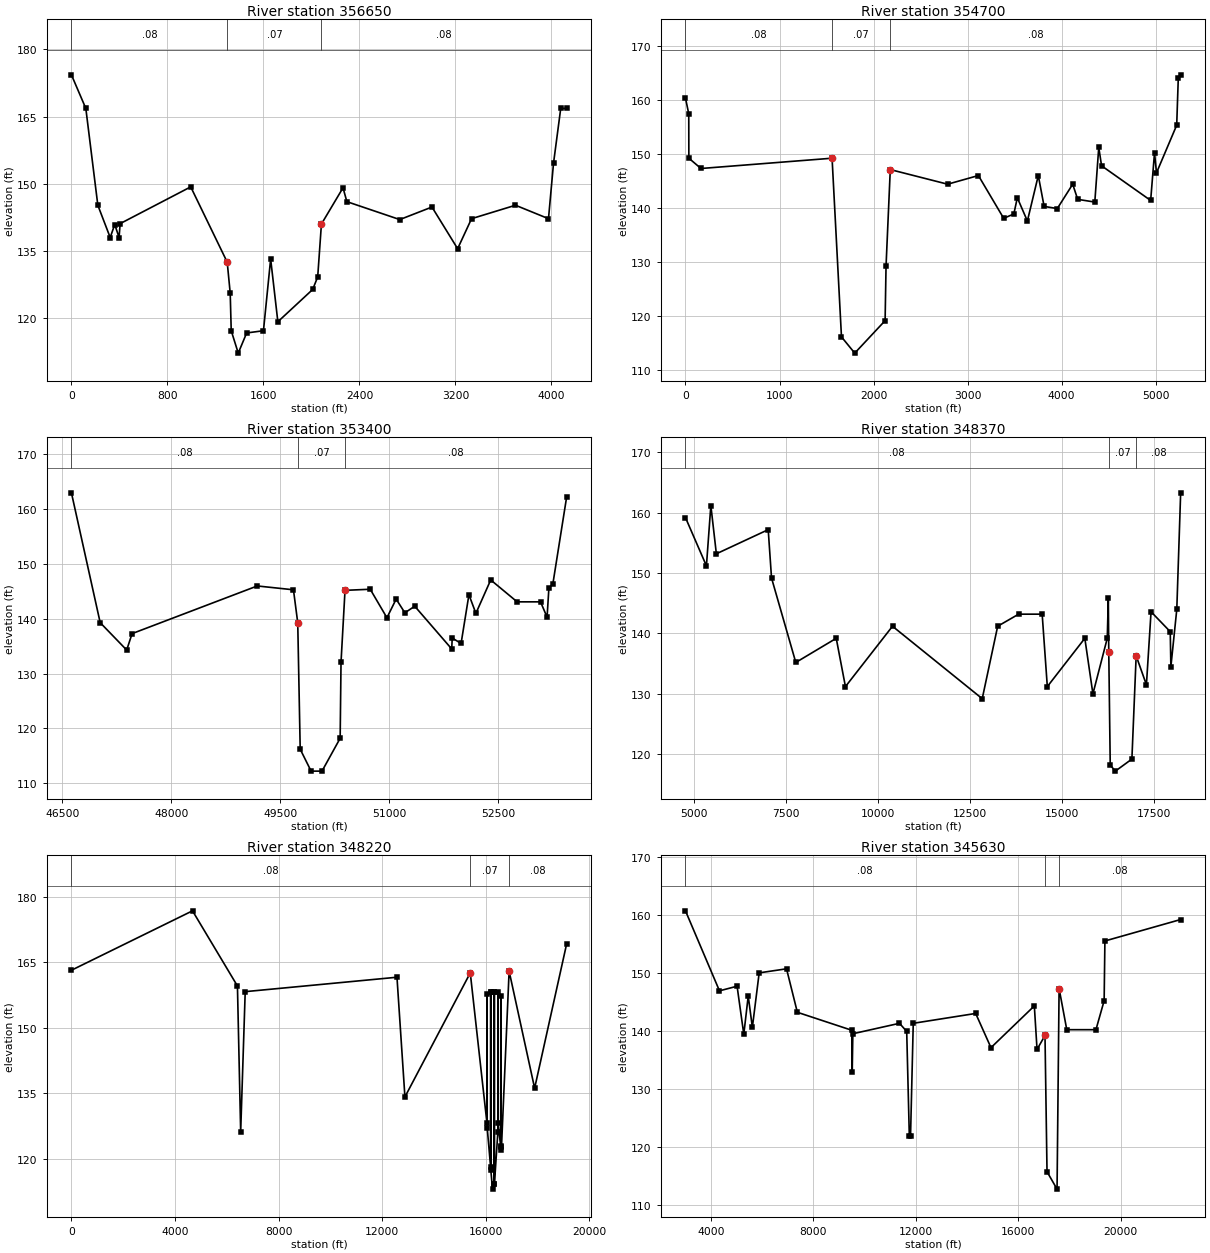
Type RM Length L Ch R = 1 ,356650  ,2400,1950,1200
#Sta/Elev= 30
       0   174.3     120   166.8     220   145.2     323     138     361   140.9
     397     138     406   141.1     994   149.3    1298   132.5    1323   125.6
  1331.5   117.2    1390   112.2    1460   116.7    1600   117.2    1660   133.2
    1720   119.2    2010   126.4    2052   129.2    2083     141    2263   149.1
    2295     146    2736     142    3004   144.8    3218   135.5    3334   142.2
    3700   145.2    3975   142.2    4017   154.6    4077   166.8    4126   166.8
#Mann= 3 , 0 , 0
       0     .08       0    1298     .07       0    2083     .08       0
Bank Sta=1298,2083
XS Rating Curve= 0 ,0
Exp/Cntr=0.3,0.1

Type RM Length L Ch R = 1 ,354700  ,1500,1300,1000
#Sta/Elev= 30
       0   160.3      35   157.4      36   149.2     165   147.3    1559   149.2
    1659   116.2    1800   113.2    2123   119.2    2133   129.3    2178   147.1
    2788   144.4    3115     146    3384   138.1    3492   138.9    3529   141.9
    3636   137.6    3752     146    3814   140.3    3954   139.9    4118   144.4
    4171   141.6    4353   141.1    4395   151.2    4425   147.8    4947   141.4
    4988   150.2    5009   146.5    5224   155.3    5241   164.1    5266   164.6
#Mann= 3 , 0 , 0
       0     .08       0    1559     .07       0    2178     .08       0
Bank Sta=1559,2178
XS Rating Curve= 0 ,0
Exp/Cntr=0.3,0.1

Type RM Length L Ch R = 1 ,353400  ,5300,5030,4000
BEGIN DESCRIPTION:
LETTERED E
END DESCRIPTION:
#Sta/Elev= 30
   46625     163   47021   139.3   47386   134.3   47460   137.3   49184     146
   49682   145.3   49741   139.3   49775   116.2   49925   112.2   50075   112.2
   50325   118.2   50337   132.1   50392   145.2   50739   145.4   50969   140.2
   51096   143.6   51216   141.1   51352   142.3   51861   134.5   51868   136.5
   51990   135.5   52098   144.4   52194     141   52398   147.1   52762   143.1
   53084   143.1   53174   140.3   53199   145.6   53254   146.4   53443   162.2
#Mann= 3 , 0 , 0
   46625     .08       0   49741     .07       0   50392     .08       0
Bank Sta=49741,50392
XS Rating Curve= 0 ,0
Exp/Cntr=0.3,0.1

Type RM Length L Ch R = 1 ,348370  ,150,150,150
#Sta/Elev= 30
    4760   159.2    5330   151.2    5450   161.2    5600   153.2    7010   157.2
    7100   149.2    7760   135.2    8860   139.2    9110   131.2   10390   141.2
   12830   129.2   13250   141.2   13820   143.2   14460   143.2   14600   131.2
   15620   139.2   15840     130   16230   139.2   16259   145.8   16271     137
   16311   118.2   16450   117.2   16900   119.2   17016   136.3   17295   131.5
   17421   143.6   17943   140.3   17960   134.5   18121     144   18226   163.3
#Mann= 3 , 0 , 0
    4760     .08       0   16271     .07       0   17016     .08       0
Bank Sta=16271,17016
XS Rating Curve= 0 ,0
Exp/Cntr=0.3,0.1

Type RM Length L Ch R = 1 ,348220  ,1400,2590,600
#Sta/Elev= 30
       0   163.2    4675   176.8    6410   159.6    6535   126.2    6710   158.3
   12570   161.6   12877   134.2   15400   162.6   16045   128.2   16052   157.7
   16053   127.2   16185   118.2   16187   158.2   16192   158.2   16194   117.4
   16260   113.1   16325   114.2   16327   158.2   16331   158.2   16333   114.3
   16466   126.2   16467   158.2   16472   128.2   16574   122.9   16580   157.4
   16581   122.7   16600     122   16900     163   17885   136.2   19120   169.2
#Mann= 3 , 0 , 0
       0     .08       0   15400     .07       0   16900     .08       0
Bank Sta=15400,16900
XS Rating Curve= 0 ,0
Exp/Cntr=0.3,0.1

Type RM Length L Ch R = 1 ,345630  ,3100,6960,1600
#Sta/Elev= 30
    3000   160.7    4329   146.9    5017   147.7    5279   139.4    5452     146
    5614   140.6    5880     150    6949   150.7    7372   143.2    9499   140.1
    9516   132.9    9540   139.5   11363   141.3   11645   139.9   11747   121.9
   11795   121.9   11901   141.3   14340     143   14938   137.1   16632   144.3
   16738   136.8   17049   139.2   17128   115.7   17520   112.7   17600   147.3
   17900   140.2   19040   140.2   19360   145.2   19390   155.5   22350   159.2
#Mann= 3 , 0 , 0
    3000     .08       0   17049     .07       0   17600     .08       0
Bank Sta=17049,17600
XS Rating Curve= 0 ,0
Exp/Cntr=0.3,0.1

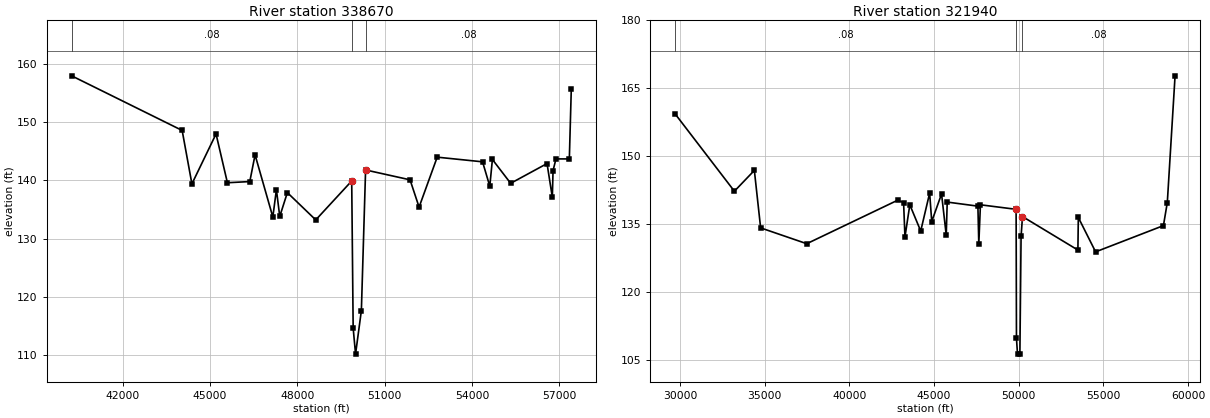
Type RM Length L Ch R = 1 ,338670  ,4300,16730,6500
BEGIN DESCRIPTION:
LETTERD D
END DESCRIPTION:
#Sta/Elev= 30
   40250     158   44045   148.6   44380   139.4   45209     148   45599   139.6
   46368   139.8   46549   144.4   47159   133.7   47282   138.4   47397   133.8
   47658   137.9   48633   133.2   49868   139.9   49918   114.6   50000   110.1
   50200   117.6   50345   141.8   51872   140.1   52182   135.4   52804     144
   54362   143.2   54610     139   54700   143.6   55327   139.5   56576   142.9
   56758   137.1   56783   141.7   56883   143.7   57342   143.7   57409   155.7
#Mann= 3 , 0 , 0
   40250     .08       0   49868     .07       0   50345     .08       0
Bank Sta=49868,50345
XS Rating Curve= 0 ,0
Exp/Cntr=0.3,0.1

Type RM Length L Ch R = 1 ,321940  ,5700,15660,4400
BEGIN DESCRIPTION:
SECTION C
END DESCRIPTION:
#Sta/Elev= 30
   29736   159.2   33216   142.2   34394   146.8   34764   134.1   37487   130.6
   42845   140.2   43202   139.7   43283   132.1   43570   139.2   44213   133.4
   44740   141.8   44863   135.5   45443   141.6   45719   132.5   45777   139.8
   47588   138.9   47641   130.5   47737   139.2   49843   138.2   49864   109.7
   49926   106.2   50066   106.2   50136   132.2   50220   136.6   53490   129.2
   53515   136.4   54535   128.8   58538   134.6   58767   139.7   59225   167.7
#Mann= 3 , 0 , 0
   29736     .08       0   49843     .07       0   50220     .08       0
Bank Sta=49843,50220
XS Rating Curve= 0 ,0
Exp/Cntr=0.3,0.1
LCMann Table=0

--- Wateree_River.g12 (geometry) ---

Geom Title=Duplicate Effective
Program Version=5.07

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
River Reach=River 1         ,Reach 1

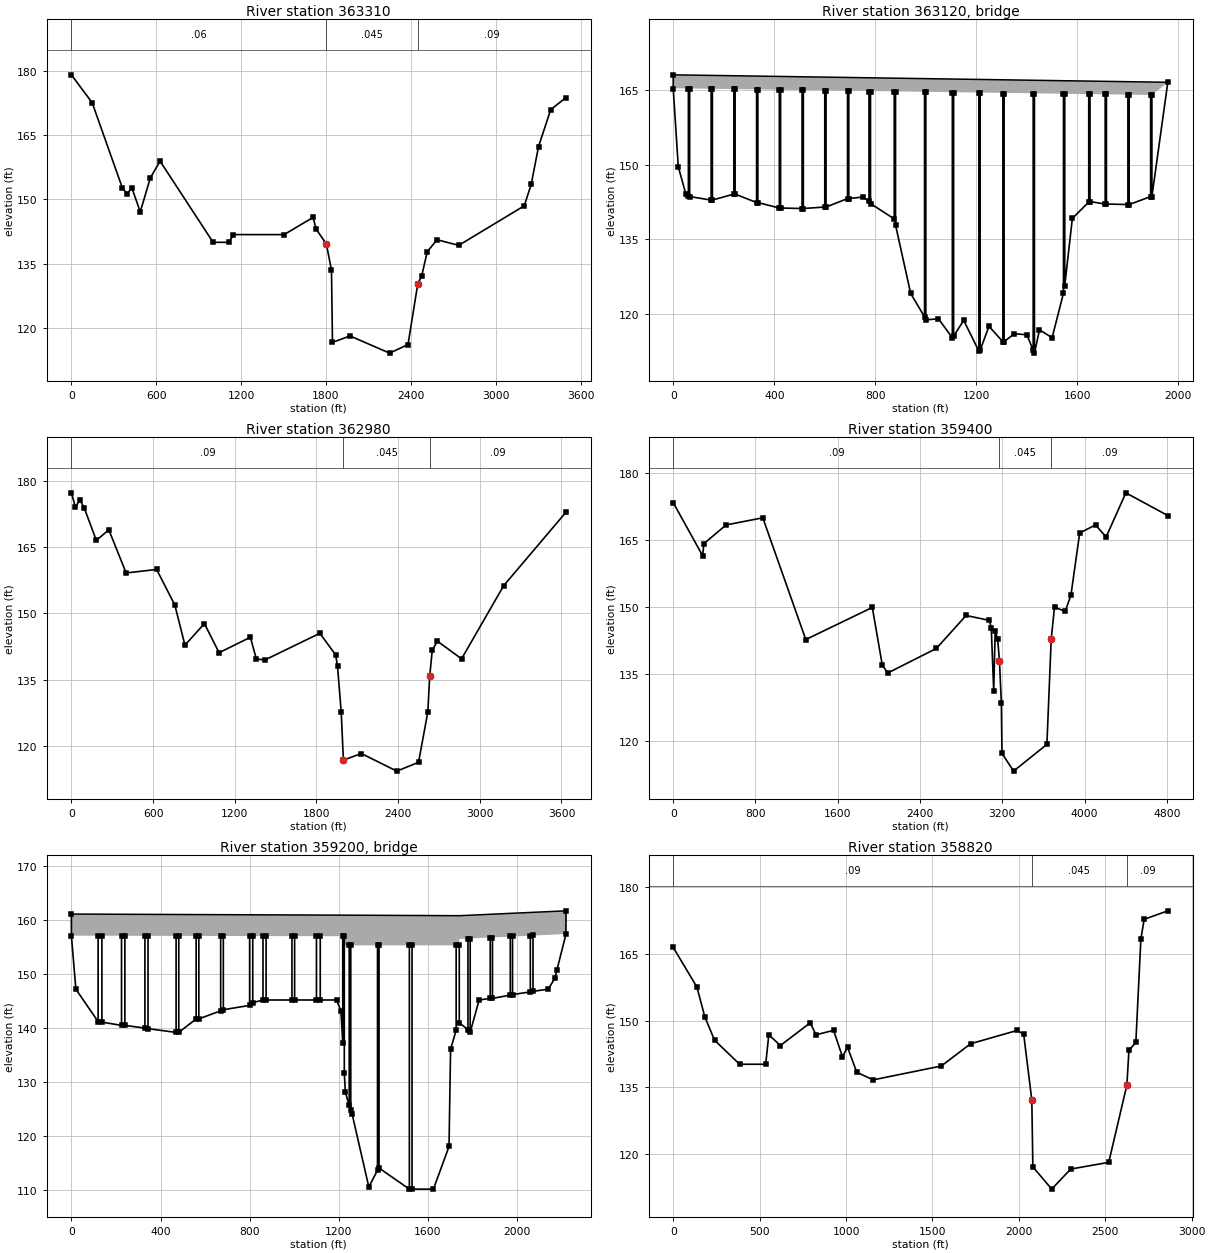
Type RM Length L Ch R = 1 ,363310  ,330,330,330
BEGIN DESCRIPTION:
LETTERED G
END DESCRIPTION:
#Sta/Elev= 30
       0     179     147   172.5     360   152.7     394   151.3     427   152.7
     487   147.1     558     155     627   158.9    1002     140    1113     140
    1146   141.8    1504   141.8    1709   145.8    1730   143.1    1803   139.6
    1839   133.5    1846   116.7    1970   118.2    2250   114.2    2380   116.2
    2449   130.3    2477   132.2    2516   137.8    2585   140.6    2739   139.3
    3202   148.5    3251   153.5    3303   162.3    3389   170.9    3497   173.7
#Mann= 3 , 0 , 0
       0     .06       0    1803    .045       0    2449     .09       0
Bank Sta=1803,2449
XS Rating Curve= 0 ,0
Exp/Cntr=0.4,0.2

Type RM Length L Ch R = 3 ,363120  ,,,
Bridge Culvert--1,0,-1,-1, 0
Deck Dist Width WeirC Skew NumUp NumDn MinLoCord MaxHiCord MaxSubmerge Is_Ogee
80,110,2.6,0, 2, 2, , , 0.98, 0, 0,0,,
       0    1958
   168.1   166.6
   165.4     164
       0    1958
   168.1   166.6
   165.4     164
BR Coef=-1 , 1 , 0 ,, 0 ,,,0.8,-1,2,0,
WSPro=,,,, 1 ,,,, 0 ,,,, 0 ,,,,-1 ,-1 ,-1 , 0 , 0 , 0 , 0 , 0
BR U #Sta/Elev= 95
       0     168       0   165.3      20   149.6      50   144.1      60   143.7
      60   165.3      65   165.3      65   143.6     150   142.9     150   165.2
     155   165.2     155   142.9     240   144.1     240   165.2     245   165.2
     245   144.1     330   142.4     330   165.1     335   165.1     335   142.4
     420   141.3     420     165     425     165     425   141.3     510   141.2
     510     165     515     165     515   141.2     600   141.5     600   164.9
     605   164.9     605   141.5     690   143.2     690   164.8     695   164.8
     695   143.2     750   143.5     775   142.7     775   164.7     781   164.7
     781   142.2     875   139.1     875   164.7     880   164.7     880   137.9
     940   124.1     995   119.4     995   164.6    1000   164.6    1000   118.8
    1050     119    1105   115.2    1105   164.5    1110   164.5    1110   115.5
    1150   118.7    1210   112.5    1210   164.4    1215   164.4    1215   112.7
    1250   117.5    1305   114.4    1305   164.3    1310   164.3    1310   114.4
    1350     116    1400   115.8    1425   112.7    1425   164.2    1430   164.2
    1430   112.1    1450   116.8    1500   115.2    1545   124.2    1545   164.2
    1550   164.2    1550   125.7    1580   139.2    1645   142.5    1645   164.2
    1650   164.2    1650   142.6    1710   142.1    1710   164.2    1715   164.2
    1715   142.1    1800     142    1800   164.1    1805   164.1    1805     142
    1890   143.6    1890     164    1895     164    1895   143.6    1958   166.6
BR U #Mann= 3
       0     .06     775     .05    1650     .06
BR U Banks=775,1650
BR D #Sta/Elev= 95
       0     168       0   165.3      20   149.6      50   144.1      60   143.7
      60   165.3      65   165.3      65   143.6     150   142.9     150   165.2
     155   165.2     155   142.9     240   144.1     240   165.2     245   165.2
     245   144.1     330   142.4     330   165.1     335   165.1     335   142.4
     420   141.3     420     165     425     165     425   141.3     510   141.2
     510     165     515     165     515   141.2     600   141.5     600   164.9
     605   164.9     605   141.5     690   143.2     690   164.8     695   164.8
     695   143.2     750   143.5     775   142.7     775   164.7     781   164.7
     781   142.2     875   139.1     875   164.7     880   164.7     880   137.9
     940   124.1     995   119.4     995   164.6    1000   164.6    1000   118.8
    1050     119    1105   115.2    1105   164.5    1110   164.5    1110   115.5
    1150   118.7    1210   112.5    1210   164.4    1215   164.4    1215   112.7
    1250   117.5    1305   114.4    1305   164.3    1310   164.3    1310   114.4
    1350     116    1400   115.8    1425   112.7    1425   164.2    1430   164.2
    1430   112.1    1450   116.8    1500   115.2    1545   124.2    1545   164.2
    1550   164.2    1550   125.7    1580   139.2    1645   142.5    1645   164.2
    1650   164.2    1650   142.6    1710   142.1    1710   164.2    1715   164.2
    1715   142.1    1800     142    1800   164.1    1805   164.1    1805     142
    1890   143.6    1890     164    1895     164    1895   143.6    1958   166.6
BR D #Mann= 3
       0     .06     775     .05    1650     .06
BR D Banks=775,1650
BC Design=,, 0 ,, 0 ,,,,,,
BC Use User HTab Curves=0
BC User HTab FreeFlow(D)= 0

Type RM Length L Ch R = 1 ,362980  ,3500,3580,3530
#Sta/Elev= 30
       0   177.4      30   174.1      62   175.8      94     174     183   166.6
     275     169     402   159.2     626     160     760   151.9     834   142.8
     977   147.7    1085   141.1    1315   144.6    1359   139.6    1425   139.5
    1825   145.5    1941   140.6    1955     138    1982   127.6    1998   116.7
    2130   118.2    2390   114.2    2550   116.2    2618   127.6    2632   135.8
    2651   141.7    2689   143.7    2866   139.7    3175   156.3    3633     173
#Mann= 3 , 0 , 0
       0     .09       0    1998    .045       0    2632     .09       0
Bank Sta=1998,2632
XS Rating Curve= 0 ,0
Exp/Cntr=0.4,0.2

Type RM Length L Ch R = 1 ,359400  ,520,580,570
#Sta/Elev= 30
       0   173.4     286   161.5     298   164.2     514   168.4     871     170
    1289   142.7    1936   149.9    2033     137    2086   135.2    2559   140.7
    2848   148.1    3075     147    3093   145.3    3117   131.1    3131   144.7
    3155   142.8    3173   137.8    3191   128.5    3197   117.2    3310   113.2
    3634   119.2    3676   142.8    3708     150    3812     149    3868   152.7
    3953   166.6    4107   168.4    4210   165.7    4402   175.6    4810   170.5
#Mann= 3 , 0 , 0
       0     .09       0    3173    .045       0    3676     .09       0
Bank Sta=3173,3676
XS Rating Curve= 0 ,0
Exp/Cntr=0.4,0.2

Type RM Length L Ch R = 3 ,359200  ,,,
Bridge Culvert--1,0,-1,-1, 0
Deck Dist Width WeirC Skew NumUp NumDn MinLoCord MaxHiCord MaxSubmerge Is_Ogee
180,20,2.6,0, 6, 6, , , 0.98, 0, 0,0,,
       0    1225    1225    1741    1741    2220
   161.1   160.9   160.9   160.8   160.8   161.7
   157.1     157   155.3   155.3   156.5   157.4
       0    1225    1225    1741    1741    2220
   161.1   160.9   160.9   160.8   160.8   161.7
   157.1     157   155.3   155.3   156.5   157.4
BR Coef=-1 , 1 , 0 ,, 0 ,,,0.8,-1,2,0,
WSPro=,,,, 1 ,,,, 0 ,,,, 0 ,,,,-1 ,-1 ,-1 , 0 , 0 , 0 , 0 , 0
BR U #Sta/Elev= 93
       0   161.1       0   157.1      20   147.2     120   141.2     120   157.1
     137   157.1     137   141.1     225   140.5     225   157.1     240   157.1
     240   140.5     330     140     330   157.1     344   157.1     344   139.9
     470   139.2     470     157     482     157     482   139.2     560   141.7
     560     157     572     157     572   141.7     670   143.2     670     157
     682     157     682   143.4     800   144.2     800     157     814     157
     814   144.7     860   145.2     860     157     874     157     874   145.2
     990   145.2     990     157    1002     157    1002   145.2    1100   145.2
    1100     157    1117     157    1117   145.2    1190   145.2    1210   143.2
    1218   137.2    1218     157    1225     157    1225   131.6    1230   128.1
    1247   125.7    1247   155.3    1254   155.3    1254   124.9    1260   124.1
    1335   110.6    1374   113.7    1374   155.3    1381   155.3    1381   114.1
    1517   110.2    1517   155.3    1529   155.3    1529   110.2    1625   110.2
    1695   118.1    1702   136.1    1727   139.6    1727   155.3    1741   155.3
    1741     141    1780   139.7    1780   156.5    1790   156.5    1790   139.2
    1830   145.2    1880   145.5    1880   156.7    1890   156.7    1890   145.5
    1970   146.1    1970     157    1980     157    1980   146.2    2060   146.7
    2060   157.1    2072   157.2    2072   146.8    2140   147.2    2170   149.2
    2179   150.7    2220   157.4    2220   161.7
BR U #Mann= 3
       0     .06    1210    .045    1741     .06
BR U Banks=1210,1741
BR D #Sta/Elev= 93
       0   161.1       0   157.1      20   147.2     120   141.2     120   157.1
     137   157.1     137   141.1     225   140.5     225   157.1     240   157.1
     240   140.5     330     140     330   157.1     344   157.1     344   139.9
     470   139.2     470     157     482     157     482   139.2     560   141.7
     560     157     572     157     572   141.7     670   143.2     670     157
     682     157     682   143.4     800   144.2     800     157     814     157
     814   144.7     860   145.2     860     157     874     157     874   145.2
     990   145.2     990     157    1002     157    1002   145.2    1100   145.2
    1100     157    1117     157    1117   145.2    1190   145.2    1210   143.2
    1218   137.2    1218     157    1225     157    1225   131.6    1230   128.1
    1247   125.7    1247   155.3    1254   155.3    1254   124.9    1260   124.1
    1335   110.6    1374   113.7    1374   155.3    1381   155.3    1381   114.1
    1517   110.2    1517   155.3    1529   155.3    1529   110.2    1625   110.2
    1695   118.1    1702   136.1    1727   139.6    1727   155.3    1741   155.3
    1741     141    1780   139.7    1780   156.5    1790   156.5    1790   139.2
    1830   145.2    1880   145.5    1880   156.7    1890   156.7    1890   145.5
    1970   146.1    1970     157    1980     157    1980   146.2    2060   146.7
    2060   157.1    2072   157.2    2072   146.8    2140   147.2    2170   149.2
    2179   150.7    2220   157.4    2220   161.7
BR D #Mann= 3
       0     .06    1210    .045    1741     .06
BR D Banks=1210,1741
BC Design=,, 0 ,, 0 ,,,,,,
BC Use User HTab Curves=0
BC User HTab FreeFlow(D)= 0

Type RM Length L Ch R = 1 ,358820  ,1800,2170,2200
BEGIN DESCRIPTION:
LETTERED F
END DESCRIPTION:
#Sta/Elev= 30
       0   166.4     137   157.5     183   150.8     239   145.6     384   140.2
     535   140.2     553   146.8     620   144.4     793   149.5     826   146.8
     928   147.8     979   141.9    1009     144    1062   138.4    1157   136.7
    1551   139.8    1721   144.8    1992   147.8    2028   146.9    2075   132.2
    2081   117.2    2190   112.2    2300   116.7    2520   118.2    2625   135.5
    2637   143.3    2677   145.1    2706   168.2    2725   172.7    2862   174.6
#Mann= 3 , 0 , 0
       0     .09       0    2075    .045       0    2625     .09       0
Bank Sta=2075,2625
XS Rating Curve= 0 ,0
Exp/Cntr=0.4,0.2

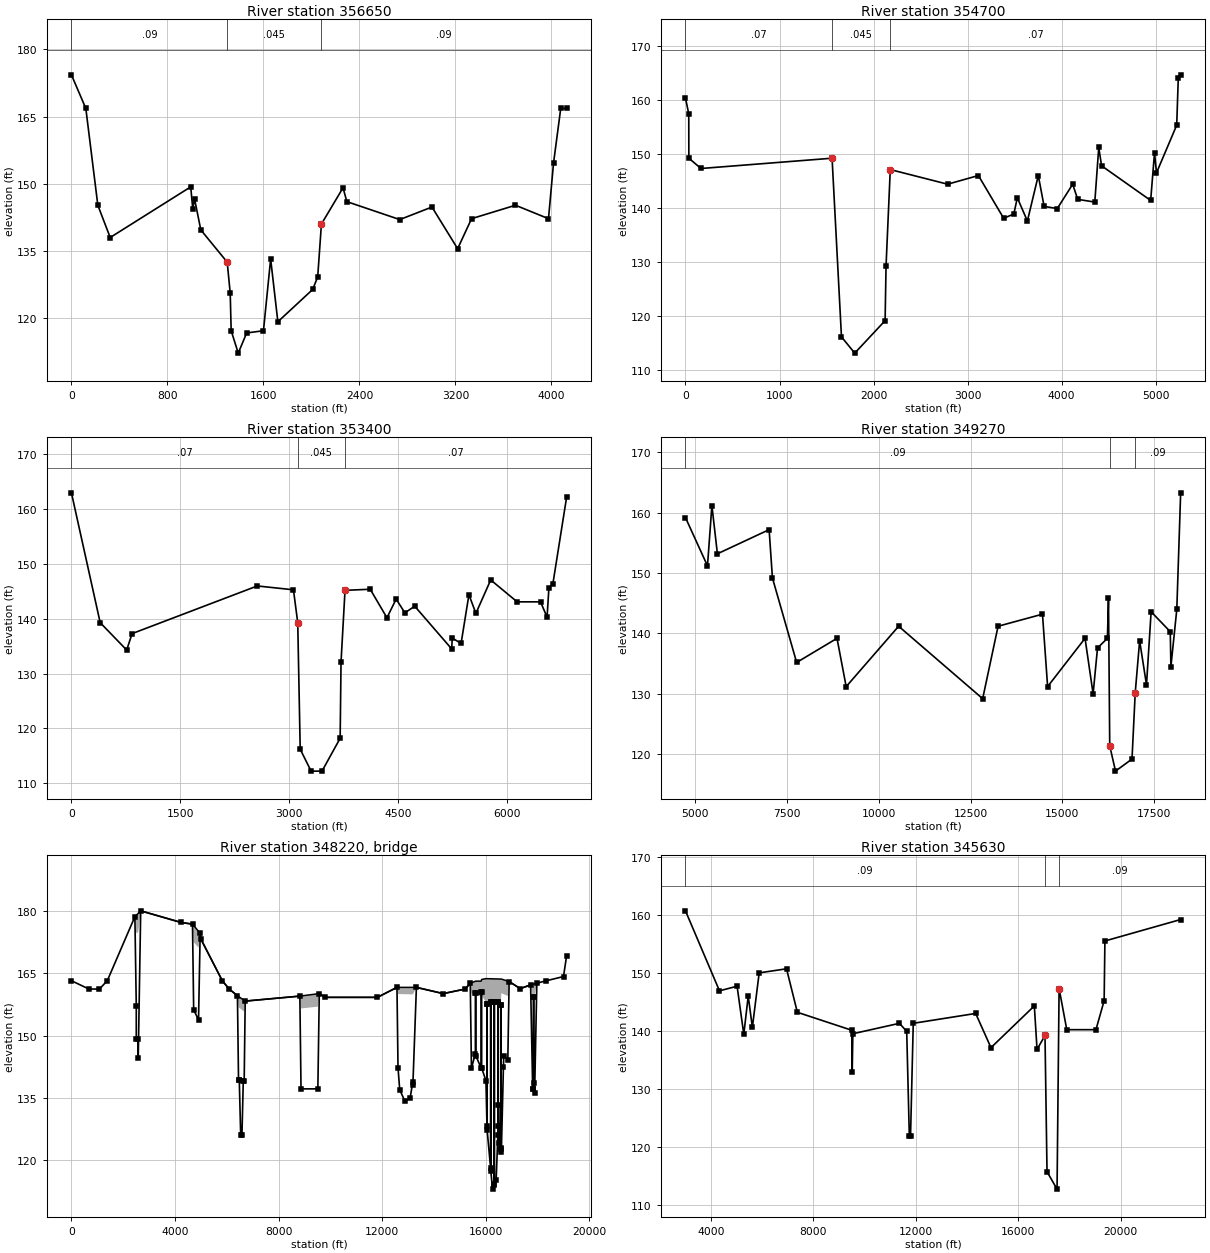
Type RM Length L Ch R = 1 ,356650  ,2400,1950,1200
#Sta/Elev= 30
       0   174.3     120   166.8     220   145.2     323     138     994   149.3
    1011   144.4    1026   146.6    1078   139.7    1298   132.5    1323   125.6
    1331   117.2    1390   112.2    1460   116.7    1600   117.2    1660   133.2
    1720   119.2    2010   126.4    2052   129.2    2083     141    2263   149.1
    2295     146    2736     142    3004   144.8    3218   135.5    3334   142.2
    3700   145.2    3975   142.2    4017   154.6    4077   166.8    4126   166.8
#Mann= 3 , 0 , 0
       0     .09       0    1298    .045       0    2083     .09       0
Bank Sta=1298,2083
XS Rating Curve= 0 ,0
Exp/Cntr=0.4,0.2

Type RM Length L Ch R = 1 ,354700  ,1500,1300,1000
#Sta/Elev= 30
       0   160.3      35   157.4      36   149.2     165   147.3    1559   149.2
    1659   116.2    1800   113.2    2123   119.2    2133   129.3    2178   147.1
    2788   144.4    3115     146    3384   138.1    3492   138.9    3529   141.9
    3636   137.6    3752     146    3814   140.3    3954   139.9    4118   144.4
    4171   141.6    4353   141.1    4395   151.2    4425   147.8    4947   141.4
    4988   150.2    5009   146.5    5224   155.3    5241   164.1    5266   164.6
#Mann= 3 , 0 , 0
       0     .07       0    1559    .045       0    2178     .07       0
Bank Sta=1559,2178
XS Rating Curve= 0 ,0
Exp/Cntr=0.4,0.2

Type RM Length L Ch R = 1 ,353400  ,4400,4130,3100
BEGIN DESCRIPTION:
LETTERED E
END DESCRIPTION:
#Sta/Elev= 30
       0     163     396   139.3     761   134.3     835   137.3    2559     146
    3057   145.3    3116   139.3    3150   116.2    3300   112.2    3450   112.2
    3700   118.2    3712   132.1    3767   145.2    4114   145.4    4344   140.2
    4471   143.6    4591   141.1    4727   142.3    5236   134.5    5243   136.5
    5365   135.5    5473   144.4    5569     141    5773   147.1    6137   143.1
    6459   143.1    6549   140.3    6574   145.6    6629   146.4    6818   162.2
#Mann= 3 , 0 , 0
       0     .07       0    3116    .045       0    3767     .07       0
Bank Sta=3116,3767
XS Rating Curve= 0 ,0
Exp/Cntr=0.4,0.2

Type RM Length L Ch R = 1 ,349270  ,3150,3640,1950
#Sta/Elev= 30
    4730   159.2    5330   151.2    5450   161.2    5600   153.2    7010   157.2
    7100   149.2    7760   135.2    8860   139.2    9110   131.2   10540   141.2
   12830   129.2   13250   141.2   14460   143.2   14600   131.2   15620   139.2
   15840     130   15960   137.6   16230   139.2   16259   145.8   16293   121.4
   16450   117.2   16900   119.2   16988   130.2   17108   138.8   17295   131.5
   17421   143.6   17943   140.3   17960   134.5   18121     144   18226   163.3
#Mann= 3 , 0 , 0
    4730     .09       0   16293    .045       0   16988     .09       0
Bank Sta=16293,16988
XS Rating Curve= 0 ,0
Exp/Cntr=0.4,0.2

Type RM Length L Ch R = 3 ,348220  ,,,
Bridge Culvert--1,0,-1,-1, 0
Deck Dist Width WeirC Skew NumUp NumDn MinLoCord MaxHiCord MaxSubmerge Is_Ogee
900,150,2.6,0, 31, 31, , , 0.98, 0, 0,0,,
    2450    2675    4235    4675    4971    5000    5825    6090    6410    6710
    6710    8820    8820    9570    9800   11815   12570   13320   14355   15205
   15400   15612   15820   15840   16005   16580   16600   16900   17330   17730
   17970
   178.6     180   177.2   176.8   174.6   173.2   163.2   161.2   159.6   158.3
   158.3   159.5   159.5   160.1   159.2   159.2   161.6   161.6   160.1   161.2
   162.6   163.1   163.1   163.5   163.7   163.6   163.6     163   161.3   162.2
   162.6
   174.4   175.2       0   172.8   170.7       0       0       0     157   155.6
       0       0   156.5     157       0       0     160   159.9       0       0
     160   160.4   159.1   159.7     158   157.4   160.2   159.4       0   159.4
   159.9
    2450    2675    4235    4675    4971    5000    5825    6090    6410    6710
    6710    8820    8820    9570    9800   11815   12570   13320   14355   15205
   15400   15612   15820   15840   16005   16580   16600   16900   17330   17730
   17970
   178.6     180   177.2   176.8   174.6   173.2   163.2   161.2   159.6   158.3
   158.3   159.5   159.5   160.1   159.2   159.2   161.6   161.6   160.1   161.2
   162.6   163.1   163.1   163.5   163.7   163.6   163.6     163   161.3   162.2
   162.6
   174.4   175.2       0   172.8   170.7       0       0       0     157   155.6
       0       0   156.5     157       0       0     160   159.9       0       0
     160   160.4   159.1   159.7     158   157.4   160.2   159.4       0   159.4
   159.9
BR Coef=-1 , 1 , 0 ,, 0 ,,,0.8,-1,2,0,
WSPro=,,,, 1 ,,,, 0 ,,,, 0 ,,,,-1 ,-1 ,-1 , 0 , 0 , 0 , 0 , 0
BR U #Sta/Elev= 94
       0   163.2     675   161.2    1080   161.2    1385   163.2    2450   178.6
    2504   157.2    2504   149.2    2565   149.2    2580   144.7    2675     180
    4235   177.2    4675   176.8    4720   156.2    4908   153.8    4971   174.6
    5000   173.2    5825   163.2    6090   161.2    6410   159.6    6452   139.4
    6481   139.3    6535   126.2    6585   126.2    6635     139    6670     139
    6710   158.3    8820   159.5    8865   137.2    9515   137.2    9570   160.1
    9800   159.2   11815   159.2   12570   161.6   12610   142.3   12676     137
   12877   134.2   13080   135.1   13180   138.8   13184   138.1   13320   161.6
   14355   160.1   15205   161.2   15400   162.6   15445   142.2   15600   145.7
   15600   160.2   15612   160.2   15612   145.2   15820   142.2   15820   160.4
   15840   160.4   15840   142.2   16005   139.2   16045   128.2   16047   157.7
   16052   157.7   16053   127.2   16185   118.2   16187   158.2   16192   158.2
   16194   117.4   16260   113.1   16325   114.2   16327   158.2   16331   158.2
   16333   114.3   16400   115.4   16466   126.2   16467   158.2   16470   158.2
   16472   128.2   16488   133.4   16525   124.2   16574   122.9   16576   157.4
   16580   157.4   16581   122.7   16600     122   16680   142.4   16695   145.2
   16850   144.2   16900     163   17330   161.3   17730   162.2   17810   137.2
   17840   137.1   17840   159.4   17850   159.4   17850   138.7   17885   136.2
   17970   162.6   18340   163.2   19000   164.2   19120   169.2
BR U #Mann= 3
       0     .06   15400     .05   16900     .06
BR U Banks=15400,16900
BR D #Sta/Elev= 94
       0   163.2     675   161.2    1080   161.2    1385   163.2    2450   178.6
    2504   157.2    2504   149.2    2565   149.2    2580   144.7    2675     180
    4235   177.2    4675   176.8    4720   156.2    4908   153.8    4971   174.6
    5000   173.2    5825   163.2    6090   161.2    6410   159.6    6452   139.4
    6481   139.3    6535   126.2    6585   126.2    6635     139    6670     139
    6710   158.3    8820   159.5    8865   137.2    9515   137.2    9570   160.1
    9800   159.2   11815   159.2   12570   161.6   12610   142.3   12676     137
   12877   134.2   13080   135.1   13180   138.8   13184   138.1   13320   161.6
   14355   160.1   15205   161.2   15400   162.6   15445   142.2   15600   145.7
   15600   160.2   15612   160.2   15612   145.2   15820   142.2   15820   160.4
   15840   160.4   15840   142.2   16005   139.2   16045   128.2   16047   157.7
   16052   157.7   16053   127.2   16185   118.2   16187   158.2   16192   158.2
   16194   117.4   16260   113.1   16325   114.2   16327   158.2   16331   158.2
   16333   114.3   16400   115.4   16466   126.2   16467   158.2   16470   158.2
   16472   128.2   16488   133.4   16525   124.2   16574   122.9   16576   157.4
   16580   157.4   16581   122.7   16600     122   16680   142.4   16695   145.2
   16850   144.2   16900     163   17330   161.3   17730   162.2   17810   137.2
   17840   137.1   17840   159.4   17850   159.4   17850   138.7   17885   136.2
   17970   162.6   18340   163.2   19000   164.2   19120   169.2
BR D #Mann= 3
       0     .06   15400     .05   16900     .06
BR D Banks=15400,16900
BC Design=,, 0 ,, 0 ,,,,,,
BC Use User HTab Curves=0
BC User HTab FreeFlow(D)= 0

Type RM Length L Ch R = 1 ,345630  ,3100,6960,1600
#Sta/Elev= 30
    3000   160.7    4329   146.9    5017   147.7    5279   139.4    5452     146
    5614   140.6    5880     150    6949   150.7    7372   143.2    9499   140.1
    9516   132.9    9540   139.5   11363   141.3   11645   139.9   11747   121.9
   11795   121.9   11901   141.3   14340     143   14938   137.1   16632   144.3
   16738   136.8   17049   139.2   17128   115.7   17520   112.7   17600   147.3
   17900   140.2   19040   140.2   19360   145.2   19390   155.5   22350   159.2
#Mann= 3 , 0 , 0
    3000     .09       0   17049    .045       0   17600     .09       0
Bank Sta=17049,17600
XS Rating Curve= 0 ,0
Exp/Cntr=0.4,0.2

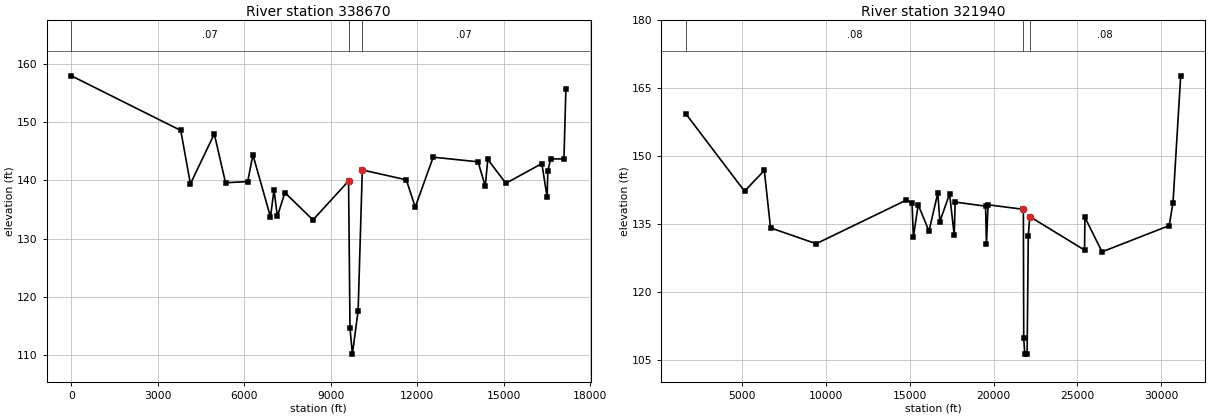
Type RM Length L Ch R = 1 ,338670  ,4300,16730,6500
BEGIN DESCRIPTION:
LETTERED D
END DESCRIPTION:
#Sta/Elev= 30
       0     158    3795   148.6    4130   139.4    4959     148    5349   139.6
    6118   139.8    6299   144.4    6909   133.7    7032   138.4    7147   133.8
    7408   137.9    8383   133.2    9618   139.9    9668   114.6    9750   110.1
    9950   117.6   10095   141.8   11622   140.1   11932   135.4   12554     144
   14112   143.2   14360     139   14450   143.6   15077   139.5   16326   142.9
   16508   137.1   16533   141.7   16633   143.7   17092   143.7   17159   155.7
#Mann= 3 , 0 , 0
       0     .07       0    9618    .045       0   10095     .07       0
Bank Sta=9618,10095
XS Rating Curve= 0 ,0
Exp/Cntr=0.4,0.2

Type RM Length L Ch R = 1 ,321940  ,5700,15660,4400
BEGIN DESCRIPTION:
LETTERED C
END DESCRIPTION:
#Sta/Elev= 30
    1670   159.2    5150   142.2    6328   146.8    6698   134.1    9421   130.6
   14779   140.2   15136   139.7   15217   132.1   15504   139.2   16147   133.4
   16674   141.8   16797   135.5   17377   141.6   17653   132.5   17711   139.8
   19522   138.9   19575   130.5   19671   139.2   21777   138.2   21798   109.7
   21860   106.2   22000   106.2   22070   132.2   22154   136.6   25424   129.2
   25449   136.4   26469   128.8   30472   134.6   30701   139.7   31159   167.7
#Mann= 3 , 0 , 0
    1670     .08       0   21777    .045       0   22154     .08       0
Bank Sta=21777,22154
XS Rating Curve= 0 ,0
Exp/Cntr=0.4,0.2
LCMann Table=0

--- Wateree_River.g13 (geometry) ---

Geom Title=Corrected Effective
Program Version=5.07

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
River Reach=River 1         ,Reach 1