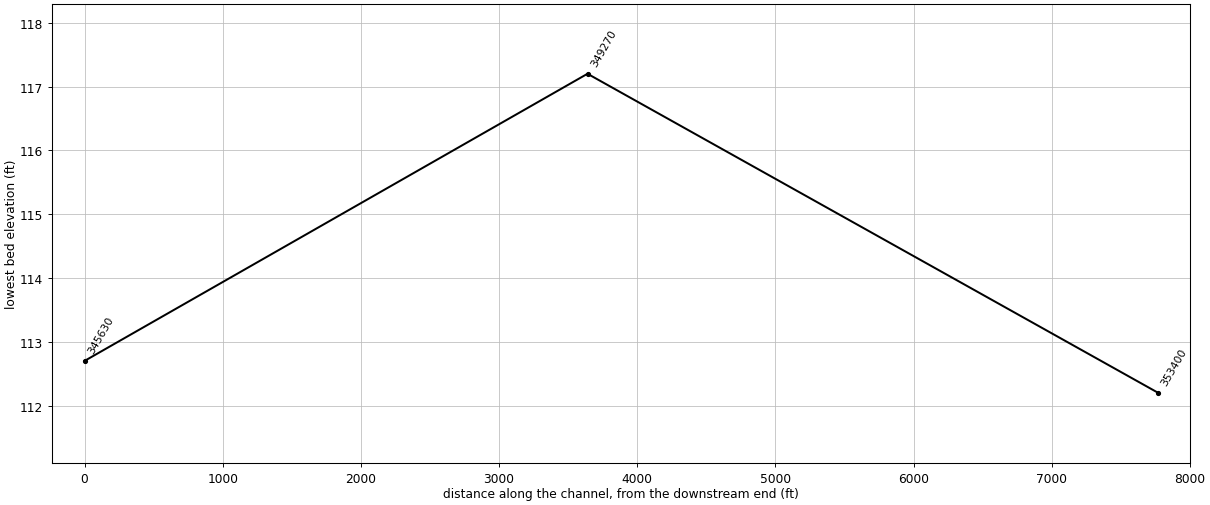
HEC-RAS study Wateree_River.prj: Wateree_River

--- Wateree_River.g13 (geometry) --- (continued)

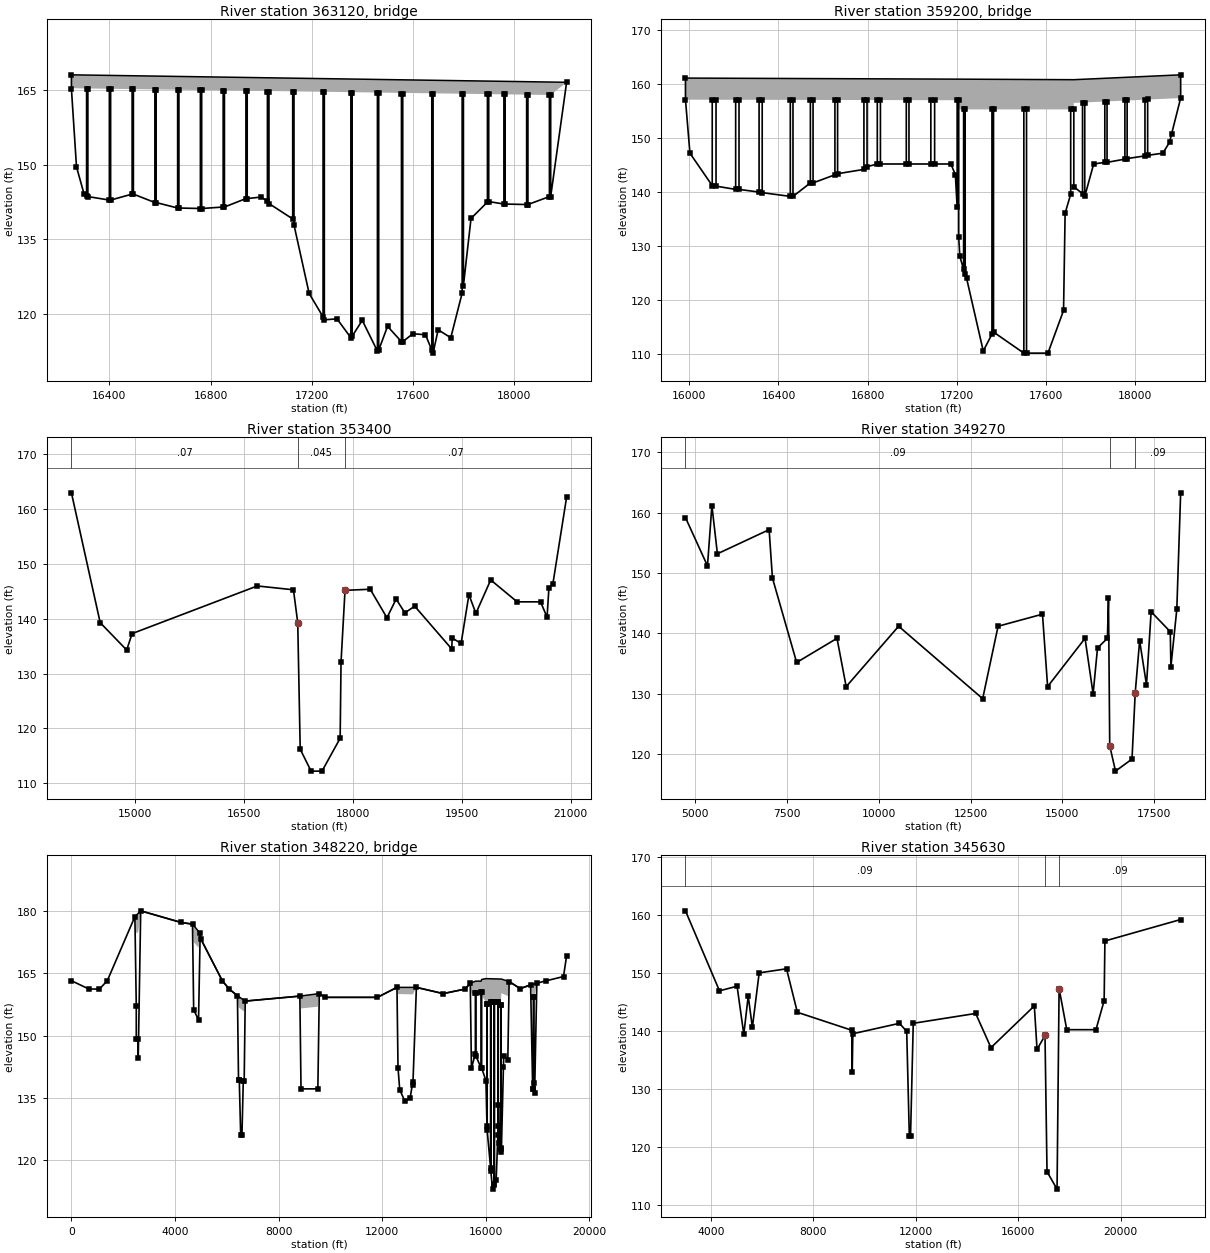
Type RM Length L Ch R = 3 ,363120  ,,,
Bridge Culvert--1,0,-1,-1, 0
Deck Dist Width WeirC Skew NumUp NumDn MinLoCord MaxHiCord MaxSubmerge Is_Ogee
80,110,2.6,0, 2, 2, , , 0.98, 0, 0,0,,
   16250   18208
   168.1   166.6
   165.4     164
   16250   18208
   168.1   166.6
   165.4     164
BR Coef=-1 , 1 , 0 ,, 0 ,,,0.8,-1,2,0,
WSPro=,,,, 1 ,,,, 0 ,,,, 0 ,,,,-1 ,-1 ,-1 , 0 , 0 , 0 , 0 , 0
BR U #Sta/Elev= 95
   16250     168   16250   165.3   16270   149.6   16300   144.1   16310   143.7
   16310   165.3   16315   165.3   16315   143.6   16400   142.9   16400   165.2
   16405   165.2   16405   142.9   16490   144.1   16490   165.2   16495   165.2
   16495   144.1   16580   142.4   16580   165.1   16585   165.1   16585   142.4
   16670   141.3   16670     165   16675     165   16675   141.3   16760   141.2
   16760     165   16765     165   16765   141.2   16850   141.5   16850   164.9
   16855   164.9   16855   141.5   16940   143.2   16940   164.8   16945   164.8
   16945   143.2   17000   143.5   17025   142.7   17025   164.7   17031   164.7
   17031   142.2   17125   139.1   17125   164.7   17130   164.7   17130   137.9
   17190   124.1   17245   119.4   17245   164.6   17250   164.6   17250   118.8
   17300     119   17355   115.2   17355   164.5   17360   164.5   17360   115.5
   17400   118.7   17460   112.5   17460   164.4   17465   164.4   17465   112.7
   17500   117.5   17555   114.4   17555   164.3   17560   164.3   17560   114.4
   17600     116   17650   115.8   17675   112.7   17675   164.2   17680   164.2
   17680   112.1   17700   116.8   17750   115.2   17795   124.2   17795   164.2
   17800   164.2   17800   125.7   17830   139.2   17895   142.5   17895   164.2
   17900   164.2   17900   142.6   17960   142.1   17960   164.2   17965   164.2
   17965   142.1   18050     142   18050   164.1   18055   164.1   18055     142
   18140   143.6   18140     164   18145     164   18145   143.6   18208   166.6
BR U #Mann= 3
   16250     .06   17025     .05   17900     .06
BR U Banks=17025,17900
BR D #Sta/Elev= 95
   16250     168   16250   165.3   16270   149.6   16300   144.1   16310   143.7
   16310   165.3   16315   165.3   16315   143.6   16400   142.9   16400   165.2
   16405   165.2   16405   142.9   16490   144.1   16490   165.2   16495   165.2
   16495   144.1   16580   142.4   16580   165.1   16585   165.1   16585   142.4
   16670   141.3   16670     165   16675     165   16675   141.3   16760   141.2
   16760     165   16765     165   16765   141.2   16850   141.5   16850   164.9
   16855   164.9   16855   141.5   16940   143.2   16940   164.8   16945   164.8
   16945   143.2   17000   143.5   17025   142.7   17025   164.7   17031   164.7
   17031   142.2   17125   139.1   17125   164.7   17130   164.7   17130   137.9
   17190   124.1   17245   119.4   17245   164.6   17250   164.6   17250   118.8
   17300     119   17355   115.2   17355   164.5   17360   164.5   17360   115.5
   17400   118.7   17460   112.5   17460   164.4   17465   164.4   17465   112.7
   17500   117.5   17555   114.4   17555   164.3   17560   164.3   17560   114.4
   17600     116   17650   115.8   17675   112.7   17675   164.2   17680   164.2
   17680   112.1   17700   116.8   17750   115.2   17795   124.2   17795   164.2
   17800   164.2   17800   125.7   17830   139.2   17895   142.5   17895   164.2
   17900   164.2   17900   142.6   17960   142.1   17960   164.2   17965   164.2
   17965   142.1   18050     142   18050   164.1   18055   164.1   18055     142
   18140   143.6   18140     164   18145     164   18145   143.6   18208   166.6
BR D #Mann= 3
   16250     .06   17025     .05   17900     .06
BR D Banks=17025,17900
BC Design=,, 0 ,, 0 ,,,,,,
BC Use User HTab Curves=0
BC User HTab FreeFlow(D)= 0

Type RM Length L Ch R = 3 ,359200  ,,,
Bridge Culvert--1,0,-1,-1, 0
Deck Dist Width WeirC Skew NumUp NumDn MinLoCord MaxHiCord MaxSubmerge Is_Ogee
180,20,2.6,0, 6, 6, , , 0.98, 0, 0,0,,
   15983   17208   17208   17724   17724   18203
   161.1   160.9   160.9   160.8   160.8   161.7
   157.1     157   155.3   155.3   156.5   157.4
   15983   17208   17208   17724   17724   18203
   161.1   160.9   160.9   160.8   160.8   161.7
   157.1     157   155.3   155.3   156.5   157.4
BR Coef=-1 , 1 , 0 ,, 0 ,,,0.8,-1,2,0,
WSPro=,,,, 1 ,,,, 0 ,,,, 0 ,,,,-1 ,-1 ,-1 , 0 , 0 , 0 , 0 , 0
BR U #Sta/Elev= 93
   15983   161.1   15983   157.1   16003   147.2   16103   141.2   16103   157.1
   16120   157.1   16120   141.1   16208   140.5   16208   157.1   16223   157.1
   16223   140.5   16313     140   16313   157.1   16327   157.1   16327   139.9
   16453   139.2   16453     157   16465     157   16465   139.2   16543   141.7
   16543     157   16555     157   16555   141.7   16653   143.2   16653     157
   16665     157   16665   143.4   16783   144.2   16783     157   16797     157
   16797   144.7   16843   145.2   16843     157   16857     157   16857   145.2
   16973   145.2   16973     157   16985     157   16985   145.2   17083   145.2
   17083     157   17100     157   17100   145.2   17173   145.2   17193   143.2
   17201   137.2   17201     157   17208     157   17208   131.6   17213   128.1
   17230   125.7   17230   155.3   17237   155.3   17237   124.9   17243   124.1
   17318   110.6   17357   113.7   17357   155.3   17364   155.3   17364   114.1
   17500   110.2   17500   155.3   17512   155.3   17512   110.2   17608   110.2
   17678   118.1   17685   136.1   17710   139.6   17710   155.3   17724   155.3
   17724     141   17763   139.7   17763   156.5   17773   156.5   17773   139.2
   17813   145.2   17863   145.5   17863   156.7   17873   156.7   17873   145.5
   17953   146.1   17953     157   17963     157   17963   146.2   18043   146.7
   18043   157.1   18055   157.2   18055   146.8   18123   147.2   18153   149.2
   18162   150.7   18203   157.4   18203   161.7
BR U #Mann= 3
   15983     .06   17193    .045   17724     .06
BR U Banks=17193,17724
BR D #Sta/Elev= 93
   15983   161.1   15983   157.1   16003   147.2   16103   141.2   16103   157.1
   16120   157.1   16120   141.1   16208   140.5   16208   157.1   16223   157.1
   16223   140.5   16313     140   16313   157.1   16327   157.1   16327   139.9
   16453   139.2   16453     157   16465     157   16465   139.2   16543   141.7
   16543     157   16555     157   16555   141.7   16653   143.2   16653     157
   16665     157   16665   143.4   16783   144.2   16783     157   16797     157
   16797   144.7   16843   145.2   16843     157   16857     157   16857   145.2
   16973   145.2   16973     157   16985     157   16985   145.2   17083   145.2
   17083     157   17100     157   17100   145.2   17173   145.2   17193   143.2
   17201   137.2   17201     157   17208     157   17208   131.6   17213   128.1
   17230   125.7   17230   155.3   17237   155.3   17237   124.9   17243   124.1
   17318   110.6   17357   113.7   17357   155.3   17364   155.3   17364   114.1
   17500   110.2   17500   155.3   17512   155.3   17512   110.2   17608   110.2
   17678   118.1   17685   136.1   17710   139.6   17710   155.3   17724   155.3
   17724     141   17763   139.7   17763   156.5   17773   156.5   17773   139.2
   17813   145.2   17863   145.5   17863   156.7   17873   156.7   17873   145.5
   17953   146.1   17953     157   17963     157   17963   146.2   18043   146.7
   18043   157.1   18055   157.2   18055   146.8   18123   147.2   18153   149.2
   18162   150.7   18203   157.4   18203   161.7
BR D #Mann= 3
   15983     .06   17193    .045   17724     .06
BR D Banks=17193,17724
BC Design=,, 0 ,, 0 ,,,,,,
BC Use User HTab Curves=0
BC User HTab FreeFlow(D)= 0

Type RM Length L Ch R = 1 ,353400  ,4400,4130,3100
BEGIN DESCRIPTION:
LETTERED E
END DESCRIPTION:
#Sta/Elev= 30
   14125     163   14521   139.3   14886   134.3   14960   137.3   16684     146
   17182   145.3   17241   139.3   17275   116.2   17425   112.2   17575   112.2
   17825   118.2   17837   132.1   17892   145.2   18239   145.4   18469   140.2
   18596   143.6   18716   141.1   18852   142.3   19361   134.5   19368   136.5
   19490   135.5   19598   144.4   19694     141   19898   147.1   20262   143.1
   20584   143.1   20674   140.3   20699   145.6   20754   146.4   20943   162.2
#Mann= 3 , 0 , 0
   14125     .07       0   17241    .045       0   17892     .07       0
Bank Sta=17241,17892
XS Rating Curve= 0 ,0
Exp/Cntr=0.3,0.1

Type RM Length L Ch R = 1 ,349270  ,3150,3640,1950
#Sta/Elev= 30
    4730   159.2    5330   151.2    5450   161.2    5600   153.2    7010   157.2
    7100   149.2    7760   135.2    8860   139.2    9110   131.2   10540   141.2
   12830   129.2   13250   141.2   14460   143.2   14600   131.2   15620   139.2
   15840     130   15960   137.6   16230   139.2   16259   145.8   16293   121.4
   16450   117.2   16900   119.2   16988   130.2   17108   138.8   17295   131.5
   17421   143.6   17943   140.3   17960   134.5   18121     144   18226   163.3
#Mann= 3 , 0 , 0
    4730     .09       0   16293    .045       0   16988     .09       0
Bank Sta=16293,16988
XS Rating Curve= 0 ,0
Exp/Cntr=0.5,0.3

Type RM Length L Ch R = 3 ,348220  ,,,
Bridge Culvert--1,0,-1,-1, 0
Deck Dist Width WeirC Skew NumUp NumDn MinLoCord MaxHiCord MaxSubmerge Is_Ogee
900,150,2.6,0, 31, 31, , , 0.98, 0, 0,0,,
    2450    2675    4235    4675    4971    5000    5825    6090    6410    6710
    6710    8820    8820    9570    9800   11815   12570   13320   14355   15205
   15400   15612   15820   15840   16005   16580   16600   16900   17330   17730
   17970
   178.6     180   177.2   176.8   174.6   173.2   163.2   161.2   159.6   158.3
   158.3   159.5   159.5   160.1   159.2   159.2   161.6   161.6   160.1   161.2
   162.6   163.1   163.1   163.5   163.7   163.6   163.6     163   161.3   162.2
   162.6
   174.4   175.2       0   172.8   170.7       0       0       0     157   155.6
       0       0   156.5     157       0       0     160   159.9       0       0
     160   160.4   159.1   159.7     158   157.4   160.2   159.4       0   159.4
   159.9
    2450    2675    4235    4675    4971    5000    5825    6090    6410    6710
    6710    8820    8820    9570    9800   11815   12570   13320   14355   15205
   15400   15612   15820   15840   16005   16580   16600   16900   17330   17730
   17970
   178.6     180   177.2   176.8   174.6   173.2   163.2   161.2   159.6   158.3
   158.3   159.5   159.5   160.1   159.2   159.2   161.6   161.6   160.1   161.2
   162.6   163.1   163.1   163.5   163.7   163.6   163.6     163   161.3   162.2
   162.6
   174.4   175.2       0   172.8   170.7       0       0       0     157   155.6
       0       0   156.5     157       0       0     160   159.9       0       0
     160   160.4   159.1   159.7     158   157.4   160.2   159.4       0   159.4
   159.9
BR Coef=-1 , 1 , 0 ,, 0 ,,,0.8,-1,2,0,
WSPro=,,,, 1 ,,,, 0 ,,,, 0 ,,,,-1 ,-1 ,-1 , 0 , 0 , 0 , 0 , 0
BR U #Sta/Elev= 94
       0   163.2     675   161.2    1080   161.2    1385   163.2    2450   178.6
    2504   157.2    2504   149.2    2565   149.2    2580   144.7    2675     180
    4235   177.2    4675   176.8    4720   156.2    4908   153.8    4971   174.6
    5000   173.2    5825   163.2    6090   161.2    6410   159.6    6452   139.4
    6481   139.3    6535   126.2    6585   126.2    6635     139    6670     139
    6710   158.3    8820   159.5    8865   137.2    9515   137.2    9570   160.1
    9800   159.2   11815   159.2   12570   161.6   12610   142.3   12676     137
   12877   134.2   13080   135.1   13180   138.8   13184   138.1   13320   161.6
   14355   160.1   15205   161.2   15400   162.6   15445   142.2   15600   145.7
   15600   160.2   15612   160.2   15612   145.2   15820   142.2   15820   160.4
   15840   160.4   15840   142.2   16005   139.2   16045   128.2   16047   157.7
   16052   157.7   16053   127.2   16185   118.2   16187   158.2   16192   158.2
   16194   117.4   16260   113.1   16325   114.2   16327   158.2   16331   158.2
   16333   114.3   16400   115.4   16466   126.2   16467   158.2   16470   158.2
   16472   128.2   16488   133.4   16525   124.2   16574   122.9   16576   157.4
   16580   157.4   16581   122.7   16600     122   16680   142.4   16695   145.2
   16850   144.2   16900     163   17330   161.3   17730   162.2   17810   137.2
   17840   137.1   17840   159.4   17850   159.4   17850   138.7   17885   136.2
   17970   162.6   18340   163.2   19000   164.2   19120   169.2
BR U #Mann= 3
       0     .06   16488     .05   16850     .06
BR U Banks=15400,16900
BR D #Sta/Elev= 94
       0   163.2     675   161.2    1080   161.2    1385   163.2    2450   178.6
    2504   157.2    2504   149.2    2565   149.2    2580   144.7    2675     180
    4235   177.2    4675   176.8    4720   156.2    4908   153.8    4971   174.6
    5000   173.2    5825   163.2    6090   161.2    6410   159.6    6452   139.4
    6481   139.3    6535   126.2    6585   126.2    6635     139    6670     139
    6710   158.3    8820   159.5    8865   137.2    9515   137.2    9570   160.1
    9800   159.2   11815   159.2   12570   161.6   12610   142.3   12676     137
   12877   134.2   13080   135.1   13180   138.8   13184   138.1   13320   161.6
   14355   160.1   15205   161.2   15400   162.6   15445   142.2   15600   145.7
   15600   160.2   15612   160.2   15612   145.2   15820   142.2   15820   160.4
   15840   160.4   15840   142.2   16005   139.2   16045   128.2   16047   157.7
   16052   157.7   16053   127.2   16185   118.2   16187   158.2   16192   158.2
   16194   117.4   16260   113.1   16325   114.2   16327   158.2   16331   158.2
   16333   114.3   16400   115.4   16466   126.2   16467   158.2   16470   158.2
   16472   128.2   16488   133.4   16525   124.2   16574   122.9   16576   157.4
   16580   157.4   16581   122.7   16600     122   16680   142.4   16695   145.2
   16850   144.2   16900     163   17330   161.3   17730   162.2   17810   137.2
   17840   137.1   17840   159.4   17850   159.4   17850   138.7   17885   136.2
   17970   162.6   18340   163.2   19000   164.2   19120   169.2
BR D #Mann= 3
       0     .06   15820     .05   16047     .06
BR D Banks=15400,16900
BC Design=,, 0 ,, 0 ,,,,,,
BC Use User HTab Curves=0
BC User HTab FreeFlow(D)= 0

Type RM Length L Ch R = 1 ,345630  ,3100,6960,1600
#Sta/Elev= 30
    3000   160.7    4329   146.9    5017   147.7    5279   139.4    5452     146
    5614   140.6    5880     150    6949   150.7    7372   143.2    9499   140.1
    9516   132.9    9540   139.5   11363   141.3   11645   139.9   11747   121.9
   11795   121.9   11901   141.3   14340     143   14938   137.1   16632   144.3
   16738   136.8   17049   139.2   17128   115.7   17520   112.7   17600   147.3
   17900   140.2   19040   140.2   19360   145.2   19390   155.5   22350   159.2
#Mann= 3 , 0 , 0
    3000     .09       0   17049    .045       0   17600     .09       0
Bank Sta=17049,17600
XS Rating Curve= 0 ,0
Exp/Cntr=0.5,0.3

--- Wateree_River.g14 (geometry) ---

Geom Title=Existing Conditions
Program Version=5.07

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
River Reach=River 1         ,Reach 1