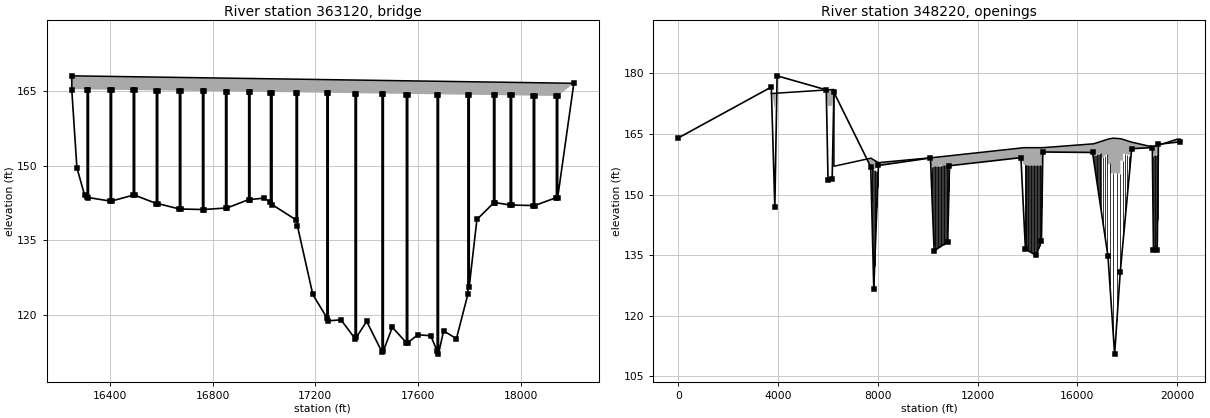
HEC-RAS study Wateree_River.prj: Wateree_River

--- Wateree_River.g14 (geometry) --- (continued)

Type RM Length L Ch R = 3 ,363120  ,,,
Bridge Culvert--1,0,-1,-1, 0
Deck Dist Width WeirC Skew NumUp NumDn MinLoCord MaxHiCord MaxSubmerge Is_Ogee
80,110,2.6,0, 2, 2, , , 0.98, 0, 0,0,,
   16250   18208
   168.1   166.6
   165.4     164
   16250   18208
   168.1   166.6
   165.4     164
BR Coef=-1 , 1 , 0 ,, 0 ,,,0.8,-1,2,0,
WSPro=,,,, 1 ,,,, 0 ,,,, 0 ,,,,-1 ,-1 ,-1 , 0 , 0 , 0 , 0 , 0
BR U #Sta/Elev= 95
   16250     168   16250   165.3   16270   149.6   16300   144.1   16310   143.7
   16310   165.3   16315   165.3   16315   143.6   16400   142.9   16400   165.2
   16405   165.2   16405   142.9   16490   144.1   16490   165.2   16495   165.2
   16495   144.1   16580   142.4   16580   165.1   16585   165.1   16585   142.4
   16670   141.3   16670     165   16675     165   16675   141.3   16760   141.2
   16760     165   16765     165   16765   141.2   16850   141.5   16850   164.9
   16855   164.9   16855   141.5   16940   143.2   16940   164.8   16945   164.8
   16945   143.2   17000   143.5   17025   142.7   17025   164.7   17031   164.7
   17031   142.2   17125   139.1   17125   164.7   17130   164.7   17130   137.9
   17190   124.1   17245   119.4   17245   164.6   17250   164.6   17250   118.8
   17300     119   17355   115.2   17355   164.5   17360   164.5   17360   115.5
   17400   118.7   17460   112.5   17460   164.4   17465   164.4   17465   112.7
   17500   117.5   17555   114.4   17555   164.3   17560   164.3   17560   114.4
   17600     116   17650   115.8   17675   112.7   17675   164.2   17680   164.2
   17680   112.1   17700   116.8   17750   115.2   17795   124.2   17795   164.2
   17800   164.2   17800   125.7   17830   139.2   17895   142.5   17895   164.2
   17900   164.2   17900   142.6   17960   142.1   17960   164.2   17965   164.2
   17965   142.1   18050     142   18050   164.1   18055   164.1   18055     142
   18140   143.6   18140     164   18145     164   18145   143.6   18208   166.6
BR U #Mann= 3
   16250     .06   17025     .05   17900     .06
BR U Banks=17025,17900
BR D #Sta/Elev= 95
   16250     168   16250   165.3   16270   149.6   16300   144.1   16310   143.7
   16310   165.3   16315   165.3   16315   143.6   16400   142.9   16400   165.2
   16405   165.2   16405   142.9   16490   144.1   16490   165.2   16495   165.2
   16495   144.1   16580   142.4   16580   165.1   16585   165.1   16585   142.4
   16670   141.3   16670     165   16675     165   16675   141.3   16760   141.2
   16760     165   16765     165   16765   141.2   16850   141.5   16850   164.9
   16855   164.9   16855   141.5   16940   143.2   16940   164.8   16945   164.8
   16945   143.2   17000   143.5   17025   142.7   17025   164.7   17031   164.7
   17031   142.2   17125   139.1   17125   164.7   17130   164.7   17130   137.9
   17190   124.1   17245   119.4   17245   164.6   17250   164.6   17250   118.8
   17300     119   17355   115.2   17355   164.5   17360   164.5   17360   115.5
   17400   118.7   17460   112.5   17460   164.4   17465   164.4   17465   112.7
   17500   117.5   17555   114.4   17555   164.3   17560   164.3   17560   114.4
   17600     116   17650   115.8   17675   112.7   17675   164.2   17680   164.2
   17680   112.1   17700   116.8   17750   115.2   17795   124.2   17795   164.2
   17800   164.2   17800   125.7   17830   139.2   17895   142.5   17895   164.2
   17900   164.2   17900   142.6   17960   142.1   17960   164.2   17965   164.2
   17965   142.1   18050     142   18050   164.1   18055   164.1   18055     142
   18140   143.6   18140     164   18145     164   18145   143.6   18208   166.6
BR D #Mann= 3
   16250     .06   17025     .05   17900     .06
BR D Banks=17025,17900
BC Design=,, 0 ,, 0 ,,,,,,
BC Use User HTab Curves=0
BC User HTab FreeFlow(D)= 0

Type RM Length L Ch R = 4 ,348220  ,,,
Bridge Culvert--1,0,-1,-1, 0
Deck Dist Width WeirC Skew NumUp NumDn MinLoCord MaxHiCord MaxSubmerge Is_Ogee
196.5,130.5,2.6,0, 38, 38, , , 0.98, 0, 0,0,,
 3730.66 3730.66 6240.82 6240.82 7722.53 7722.53 8022.53 8022.53   10130   10130
   10880   10880   13860   13860   14610   1461016653.8416653.8416923.8416953.84
16953.8417194.4717194.4717303.8517303.8517443.8517723.8517723.8517833.2317833.23
17913.8618153.8418153.8419004.6219004.6219244.62   2000020126.23
     175     175     176     157     159     159   157.9   157.9   159.1   159.1
   159.6   159.6   161.6   161.6   161.6   161.6  162.56  162.56   163.1  163.16
  163.16  163.64  163.64  163.82  163.82  163.95  163.82  163.82  163.64  163.64
  163.48     163     163   161.8   161.8   162.2   163.7   163.7
             171     172                   156.6   155.5                   156.9
   157.4                   157.3   157.3   157.3       0  159.66   160.2  160.26
   158.9     160   157.4   157.7   155.2   155.3   155.2  158.48   158.3   160.2
     160   159.2       0           159.6   160.1   157.1
 3730.66 3730.66 6240.82 6240.82 7722.53 7722.53 8022.53 8022.53   10130   10130
   10880   10880   13860   13860   14610   1461016653.8416653.8416923.8416953.84
16953.8417194.4717194.4717303.8517303.8517443.8517723.8517723.8517833.2317833.23
17913.8618153.8418153.8419004.6219004.6219244.62   2000020126.23
     175     175     176     157     159     159   157.9   157.9   159.1   159.1
   159.6   159.6   161.6   161.6   161.6   161.6  162.56  162.56   163.1  163.16
  163.16  163.64  163.64  163.82  163.82  163.95  163.82  163.82  163.64  163.64
  163.48     163     163   161.8   161.8   162.2   163.7   163.7
             171     172                   156.6   155.5                   156.9
   157.4                   157.3   157.3   157.3       0  159.66   160.2  160.26
   158.9     160   157.4   157.7   155.2   155.3   155.2  158.48   158.3   160.2
     160   159.2       0           159.6   160.1   157.1
Pier Skew, UpSta & Num, DnSta & Num=  ,7752.53, 2 ,7752.53, 2 , 0 , 0 , 0 ,,
     1.3     1.3
     120     162
     1.3     1.3
     120     162
Pier Skew, UpSta & Num, DnSta & Num=  ,7782.53, 2 ,7782.53, 2 , 0 , 0 , 0 ,,
     1.3     1.3
     120     162
     1.3     1.3
     120     162
Pier Skew, UpSta & Num, DnSta & Num=  ,7812.53, 2 ,7812.53, 2 , 0 , 0 , 0 ,,
     1.3     1.3
     120     162
     1.3     1.3
     120     162
Pier Skew, UpSta & Num, DnSta & Num=  ,7842.53, 2 ,7842.53, 2 , 0 , 0 , 0 ,,
     1.3     1.3
     120     162
     1.3     1.3
     120     162
Pier Skew, UpSta & Num, DnSta & Num=  ,7872.53, 2 ,7872.53, 2 , 0 , 0 , 0 ,,
     1.3     1.3
     120     162
     1.3     1.3
     120     162
Pier Skew, UpSta & Num, DnSta & Num=  ,7902.53, 2 ,7902.53, 2 , 0 , 0 , 0 ,,
     1.3     1.3
     120     162
     1.3     1.3
     120     162
Pier Skew, UpSta & Num, DnSta & Num=  ,7932.53, 2 ,7932.53, 2 , 0 , 0 , 0 ,,
     1.3     1.3
     120     162
     1.3     1.3
     120     162
Pier Skew, UpSta & Num, DnSta & Num=  ,7962.53, 2 ,7962.53, 2 , 0 , 0 , 0 ,,
     1.3     1.3
     120     162
     1.3     1.3
     120     162
Pier Skew, UpSta & Num, DnSta & Num=  ,7992.53, 2 ,7992.53, 2 , 0 , 0 , 0 ,,
     1.3     1.3
     120     162
     1.3     1.3
     120     162
Pier Skew, UpSta & Num, DnSta & Num=  ,10160, 2 ,10160, 2 , 0 , 0 , 0 ,,
     1.3     1.3
     120     162
     1.3     1.3
     120     162
Pier Skew, UpSta & Num, DnSta & Num=  ,10190, 2 ,10190, 2 , 0 , 0 , 0 ,,
     1.3     1.3
     120     162
     1.3     1.3
     120     162
Pier Skew, UpSta & Num, DnSta & Num=  ,10220, 2 ,10220, 2 , 0 , 0 , 0 ,,
     1.3     1.3
     120     162
     1.3     1.3
     120     162
Pier Skew, UpSta & Num, DnSta & Num=  ,10250, 2 ,10250, 2 , 0 , 0 , 0 ,,
     1.3     1.3
     120     162
     1.3     1.3
     120     162
Pier Skew, UpSta & Num, DnSta & Num=  ,10280, 2 ,10280, 2 , 0 , 0 , 0 ,,
     1.3     1.3
     120     162
     1.3     1.3
     120     162
Pier Skew, UpSta & Num, DnSta & Num=  ,10310, 2 ,10310, 2 , 0 , 0 , 0 ,,
     1.3     1.3
     120     162
     1.3     1.3
     120     162
Pier Skew, UpSta & Num, DnSta & Num=  ,10340, 2 ,10340, 2 , 0 , 0 , 0 ,,
     1.3     1.3
     120     162
     1.3     1.3
     120     162
Pier Skew, UpSta & Num, DnSta & Num=  ,10370, 2 ,10370, 2 , 0 , 0 , 0 ,,
     1.3     1.3
     120     162
     1.3     1.3
     120     162
Pier Skew, UpSta & Num, DnSta & Num=  ,10400, 2 ,10400, 2 , 0 , 0 , 0 ,,
     1.3     1.3
     120     162
     1.3     1.3
     120     162
Pier Skew, UpSta & Num, DnSta & Num=  ,10430, 2 ,10430, 2 , 0 , 0 , 0 ,,
     1.3     1.3
     120     162
     1.3     1.3
     120     162
Pier Skew, UpSta & Num, DnSta & Num=  ,10460, 2 ,10460, 2 , 0 , 0 , 0 ,,
     1.3     1.3
     120     162
     1.3     1.3
     120     162
Pier Skew, UpSta & Num, DnSta & Num=  ,10490, 2 ,10490, 2 , 0 , 0 , 0 ,,
       5       5
     120     162
       5       5
     120     162
Pier Skew, UpSta & Num, DnSta & Num=  ,10520, 2 ,10520, 2 , 0 , 0 , 0 ,,
     1.3     1.3
     120     162
     1.3     1.3
     120     162
Pier Skew, UpSta & Num, DnSta & Num=  ,10550, 2 ,10550, 2 , 0 , 0 , 0 ,,
     1.3     1.3
     120     162
     1.3     1.3
     120     162
Pier Skew, UpSta & Num, DnSta & Num=  ,10580, 2 ,10580, 2 , 0 , 0 , 0 ,,
     1.3     1.3
     120     162
     1.3     1.3
     120     162
Pier Skew, UpSta & Num, DnSta & Num=  ,10610, 2 ,10610, 2 , 0 , 0 , 0 ,,
     1.3     1.3
     120     162
     1.3     1.3
     120     162
Pier Skew, UpSta & Num, DnSta & Num=  ,10640, 2 ,10640, 2 , 0 , 0 , 0 ,,
     1.3     1.3
     120     162
     1.3     1.3
     120     162
Pier Skew, UpSta & Num, DnSta & Num=  ,10670, 2 ,10670, 2 , 0 , 0 , 0 ,,
     1.3     1.3
     120     162
     1.3     1.3
     120     162
Pier Skew, UpSta & Num, DnSta & Num=  ,10700, 2 ,10700, 2 , 0 , 0 , 0 ,,
     1.3     1.3
     120     162
     1.3     1.3
     120     162
Pier Skew, UpSta & Num, DnSta & Num=  ,10730, 2 ,10730, 2 , 0 , 0 , 0 ,,
     1.3     1.3
     120     162
     1.3     1.3
     120     162
Pier Skew, UpSta & Num, DnSta & Num=  ,10760, 2 ,10760, 2 , 0 , 0 , 0 ,,
     1.3     1.3
     120     162
     1.3     1.3
     120     162
Pier Skew, UpSta & Num, DnSta & Num=  ,10790, 2 ,10790, 2 , 0 , 0 , 0 ,,
     1.3     1.3
     120     162
     1.3     1.3
     120     162
Pier Skew, UpSta & Num, DnSta & Num=  ,10820, 2 ,10820, 2 , 0 , 0 , 0 ,,
     1.3     1.3
     120     162
     1.3     1.3
     120     162
Pier Skew, UpSta & Num, DnSta & Num=  ,10850, 2 ,10850, 2 , 0 , 0 , 0 ,,
     1.3     1.3
     120     162
     1.3     1.3
     120     162
Pier Skew, UpSta & Num, DnSta & Num=  ,13890, 2 ,13890, 2 , 0 , 0 , 0 ,,
     1.3     1.3
     120     162
     1.3     1.3
     120     162
Pier Skew, UpSta & Num, DnSta & Num=  ,13920, 2 ,13920, 2 , 0 , 0 , 0 ,,
     1.3     1.3
     120     162
     1.3     1.3
     120     162
Pier Skew, UpSta & Num, DnSta & Num=  ,13950, 2 ,13950, 2 , 0 , 0 , 0 ,,
     1.3     1.3
     120     162
     1.3     1.3
     120     162
Pier Skew, UpSta & Num, DnSta & Num=  ,13980, 2 ,13980, 2 , 0 , 0 , 0 ,,
     1.3     1.3
     120     162
     1.3     1.3
     120     162
Pier Skew, UpSta & Num, DnSta & Num=  ,14010, 2 ,14010, 2 , 0 , 0 , 0 ,,
     1.3     1.3
     120     162
     1.3     1.3
     120     162
Pier Skew, UpSta & Num, DnSta & Num=  ,14040, 2 ,14040, 2 , 0 , 0 , 0 ,,
     1.3     1.3
     120     162
     1.3     1.3
     120     162
Pier Skew, UpSta & Num, DnSta & Num=  ,14070, 2 ,14070, 2 , 0 , 0 , 0 ,,
     1.3     1.3
     120     162
     1.3     1.3
     120     162
Pier Skew, UpSta & Num, DnSta & Num=  ,14100, 2 ,14100, 2 , 0 , 0 , 0 ,,
     1.3     1.3
     120     162
     1.3     1.3
     120     162
Pier Skew, UpSta & Num, DnSta & Num=  ,14130, 2 ,14130, 2 , 0 , 0 , 0 ,,
     1.3     1.3
     120     162
     1.3     1.3
     120     162
Pier Skew, UpSta & Num, DnSta & Num=  ,14160, 2 ,14160, 2 , 0 , 0 , 0 ,,
     1.3     1.3
     120     162
     1.3     1.3
     120     162
Pier Skew, UpSta & Num, DnSta & Num=  ,14190, 2 ,14190, 2 , 0 , 0 , 0 ,,
     1.3     1.3
     120     162
     1.3     1.3
     120     162
Pier Skew, UpSta & Num, DnSta & Num=  ,14220, 2 ,14220, 2 , 0 , 0 , 0 ,,
     1.3     1.3
     120     162
     1.3     1.3
     120     162
Pier Skew, UpSta & Num, DnSta & Num=  ,14250, 2 ,14250, 2 , 0 , 0 , 0 ,,
       5       5
     120     162
       5       5
     120     162
Pier Skew, UpSta & Num, DnSta & Num=  ,14280, 2 ,14280, 2 , 0 , 0 , 0 ,,
     1.3     1.3
     120     162
     1.3     1.3
     120     162
Pier Skew, UpSta & Num, DnSta & Num=  ,14310, 2 ,14310, 2 , 0 , 0 , 0 ,,
     1.3     1.3
     120     162
     1.3     1.3
     120     162
Pier Skew, UpSta & Num, DnSta & Num=  ,14340, 2 ,14340, 2 , 0 , 0 , 0 ,,
     1.3     1.3
     120     162
     1.3     1.3
     120     162
Pier Skew, UpSta & Num, DnSta & Num=  ,14370, 2 ,14370, 2 , 0 , 0 , 0 ,,
     1.3     1.3
     120     162
     1.3     1.3
     120     162
Pier Skew, UpSta & Num, DnSta & Num=  ,14400, 2 ,14400, 2 , 0 , 0 , 0 ,,
     1.3     1.3
     120     162
     1.3     1.3
     120     162
Pier Skew, UpSta & Num, DnSta & Num=  ,14430, 2 ,14430, 2 , 0 , 0 , 0 ,,
     1.3     1.3
     120     162
     1.3     1.3
     120     162
Pier Skew, UpSta & Num, DnSta & Num=  ,14460, 2 ,14460, 2 , 0 , 0 , 0 ,,
     1.3     1.3
     120     162
     1.3     1.3
     120     162
Pier Skew, UpSta & Num, DnSta & Num=  ,14490, 2 ,14490, 2 , 0 , 0 , 0 ,,
     1.3     1.3
     120     162
     1.3     1.3
     120     162
Pier Skew, UpSta & Num, DnSta & Num=  ,14520, 2 ,14520, 2 , 0 , 0 , 0 ,,
     1.3     1.3
     120     162
     1.3     1.3
     120     162
Pier Skew, UpSta & Num, DnSta & Num=  ,14550, 2 ,14550, 2 , 0 , 0 , 0 ,,
     1.3     1.3
     120     162
     1.3     1.3
     120     162
Pier Skew, UpSta & Num, DnSta & Num=  ,14580, 2 ,14580, 2 , 0 , 0 , 0 ,,
     1.3     1.3
     120     162
     1.3     1.3
     120     162
Pier Skew, UpSta & Num, DnSta & Num=  ,16683.84, 2 ,16683.84, 2 , 0 , 0 , 0 ,,
     1.3     1.3
     120     162
     1.3     1.3
     120     162
Pier Skew, UpSta & Num, DnSta & Num=  ,16713.84, 2 ,16713.84, 2 , 0 , 0 , 0 ,,
     1.3     1.3
     120     162
     1.3     1.3
     120     162
Pier Skew, UpSta & Num, DnSta & Num=  ,16743.84, 2 ,16743.84, 2 , 0 , 0 , 0 ,,
     1.3     1.3
     120     162
     1.3     1.3
     120     162
Pier Skew, UpSta & Num, DnSta & Num=  ,16773.84, 2 ,16773.84, 2 , 0 , 0 , 0 ,,
     1.3     1.3
     120     162
     1.3     1.3
     120     162
Pier Skew, UpSta & Num, DnSta & Num=  ,16803.84, 2 ,16803.84, 2 , 0 , 0 , 0 ,,
     1.3     1.3
     120     162
     1.3     1.3
     120     162
Pier Skew, UpSta & Num, DnSta & Num=  ,16833.84, 2 ,16833.84, 2 , 0 , 0 , 0 ,,
     1.3     1.3
     120     162
     1.3     1.3
     120     162
Pier Skew, UpSta & Num, DnSta & Num=  ,16863.84, 2 ,16863.84, 2 , 0 , 0 , 0 ,,
     1.3     1.3
     120     162
     1.3     1.3
     120     162
Pier Skew, UpSta & Num, DnSta & Num=  ,16893.84, 2 ,16893.84, 2 , 0 , 0 , 0 ,,
     1.3     1.3
     120     162
     1.3     1.3
     120     162
Pier Skew, UpSta & Num, DnSta & Num=  ,16923.84, 2 ,16923.84, 2 , 0 , 0 , 0 ,,
     1.3     1.3
     120     162
     1.3     1.3
     120     162
Pier Skew, UpSta & Num, DnSta & Num=  ,16953.84, 2 ,16953.84, 2 , 0 , 0 , 0 ,,
     4.5     4.5
     120     162
     4.5     4.5
     120     162
Pier Skew, UpSta & Num, DnSta & Num=  ,17033.84, 2 ,17033.84, 2 , 0 , 0 , 0 ,,
     4.5     4.5
     120     162
     4.5     4.5
     120     162
Pier Skew, UpSta & Num, DnSta & Num=  ,17113.84, 2 ,17113.84, 2 , 0 , 0 , 0 ,,
       5       5
     120     162
       5       5
     120     162
Pier Skew, UpSta & Num, DnSta & Num=  ,17194.47, 2 ,17194.47, 2 , 0 , 0 , 0 ,,
    5.83    5.83
     120     162
    5.83    5.83
     120     162
Pier Skew, UpSta & Num, DnSta & Num=  ,17303.85, 2 ,17303.85, 2 , 0 , 0 , 0 ,,
    5.71    5.71
     120     162
    5.71    5.71
     120     162
Pier Skew, UpSta & Num, DnSta & Num=  ,17443.85, 2 ,17443.85, 2 , 0 , 0 , 0 ,,
    5.71    5.71
     120     162
    5.71    5.71
     120     162
Pier Skew, UpSta & Num, DnSta & Num=  ,17583.85, 2 ,17583.85, 2 , 0 , 0 , 0 ,,
    5.71    5.71
     120     162
    5.71    5.71
     120     162
Pier Skew, UpSta & Num, DnSta & Num=  ,17723.85, 2 ,17723.85, 2 , 0 , 0 , 0 ,,
    5.71    5.71
     120     162
    5.71    5.71
     120     162
Pier Skew, UpSta & Num, DnSta & Num=  ,17833.23, 2 ,17833.23, 2 , 0 , 0 , 0 ,,
    5.83    5.83
     120     162
    5.83    5.83
     120     162
Pier Skew, UpSta & Num, DnSta & Num=  ,17913.86, 2 ,17913.86, 2 , 0 , 0 , 0 ,,
     5.5     5.5
     120     162
     5.5     5.5
     120     162
Pier Skew, UpSta & Num, DnSta & Num=  ,17993.86, 2 ,17993.86, 2 , 0 , 0 , 0 ,,
       5       5
     120     162
       5       5
     120     162
Pier Skew, UpSta & Num, DnSta & Num=  ,18073.86, 2 ,18073.86, 2 , 0 , 0 , 0 ,,
     4.5     4.5
     120     162
     4.5     4.5
     120     162
Pier Skew, UpSta & Num, DnSta & Num=  ,19034.62, 2 ,19034.62, 2 , 0 , 0 , 0 ,,
     1.3     1.3
     120     162
     1.3     1.3
     120     162
Pier Skew, UpSta & Num, DnSta & Num=  ,19064.62, 2 ,19064.62, 2 , 0 , 0 , 0 ,,
     1.3     1.3
     120     162
     1.3     1.3
     120     162
Pier Skew, UpSta & Num, DnSta & Num=  ,19094.62, 2 ,19094.62, 2 , 0 , 0 , 0 ,,
     1.3     1.3
     120     162
     1.3     1.3
     120     162
Pier Skew, UpSta & Num, DnSta & Num=  ,19124.62, 2 ,19124.62, 2 , 0 , 0 , 0 ,,
     1.3     1.3
     120     162
     1.3     1.3
     120     162
Pier Skew, UpSta & Num, DnSta & Num=  ,19154.62, 2 ,19154.62, 2 , 0 , 0 , 0 ,,
     1.3     1.3
     120     162
     1.3     1.3
     120     162
Pier Skew, UpSta & Num, DnSta & Num=  ,19184.62, 2 ,19184.62, 2 , 0 , 0 , 0 ,,
     1.3     1.3
     120     162
     1.3     1.3
     120     162
Pier Skew, UpSta & Num, DnSta & Num=  ,19214.62, 2 ,19214.62, 2 , 0 , 0 , 0 ,,
     1.3     1.3
     120     162
     1.3     1.3
     120     162
BR Coef=-1 , 1 , 0 ,, 0 ,,,0.8,-1,2,0,
WSPro=,,,, 1 ,,,, 0 ,,,, 0 ,,,,-1 ,-1 ,-1 , 0 , 0 , 0 , 0 , 0
BC Mult= 3 ,-200,9000,-200,9000
BC Mult= 3 ,8500,12500,8500,12500
BC Mult= 3 ,12000,16000,12000,16000
BC Mult= 3 ,15500,19000,15500,19000
BC Mult= 3 ,18500,23000,18500,23000
BR U #Sta/Elev= 30
       0 164.0063730.661 176.599 3871.92 146.838 3962.73 179.375 5933.39 175.911
6003.947 153.6976170.261 153.8536240.819 175.3017717.487 156.8587838.443 126.696
8024.917 157.196 10111.6 159.05510257.82 136.10810802.68 138.29710872.98 157.143
13737.38 159.131 13917.6   136.5 14343.6  134.9614559.11 138.49414614.24 160.531
16607.68  160.4217225.88 134.77917492.77 110.52817717.63 130.79118177.96 161.345
19004.62 161.633 19050.7   136.219201.37   136.219248.12 162.45220126.23 163.047
BR U #Mann= 3
       0     .0617225.88     .0517717.63     .06
BR U Banks=17225.88,17717.63
BR D #Sta/Elev= 30
       0 164.0063730.661 176.599 3871.92 146.838 3962.73 179.375 5933.39 175.911
6003.947 153.6976170.261 153.8536240.819 175.3017717.487 156.8587838.443 126.696
8024.917 157.196 10111.6 159.05510257.82 136.10810802.68 138.29710872.98 157.143
13737.38 159.131 13917.6   136.5 14343.6  134.9614559.11 138.49414614.24 160.531
16607.68  160.4217225.88 134.77917492.77 110.52817717.63 130.79118177.96 161.345
19004.62 161.633 19050.7   136.219201.37   136.219248.12 162.45220126.23 163.047
BR D #Mann= 3
       0     .0617225.88     .0517717.63     .06
BR D Banks=17225.88,17717.63
BC Design=,, 0 ,, 0 ,,,,,,
BC Use User HTab Curves=0
BC User HTab FreeFlow(D)= 0